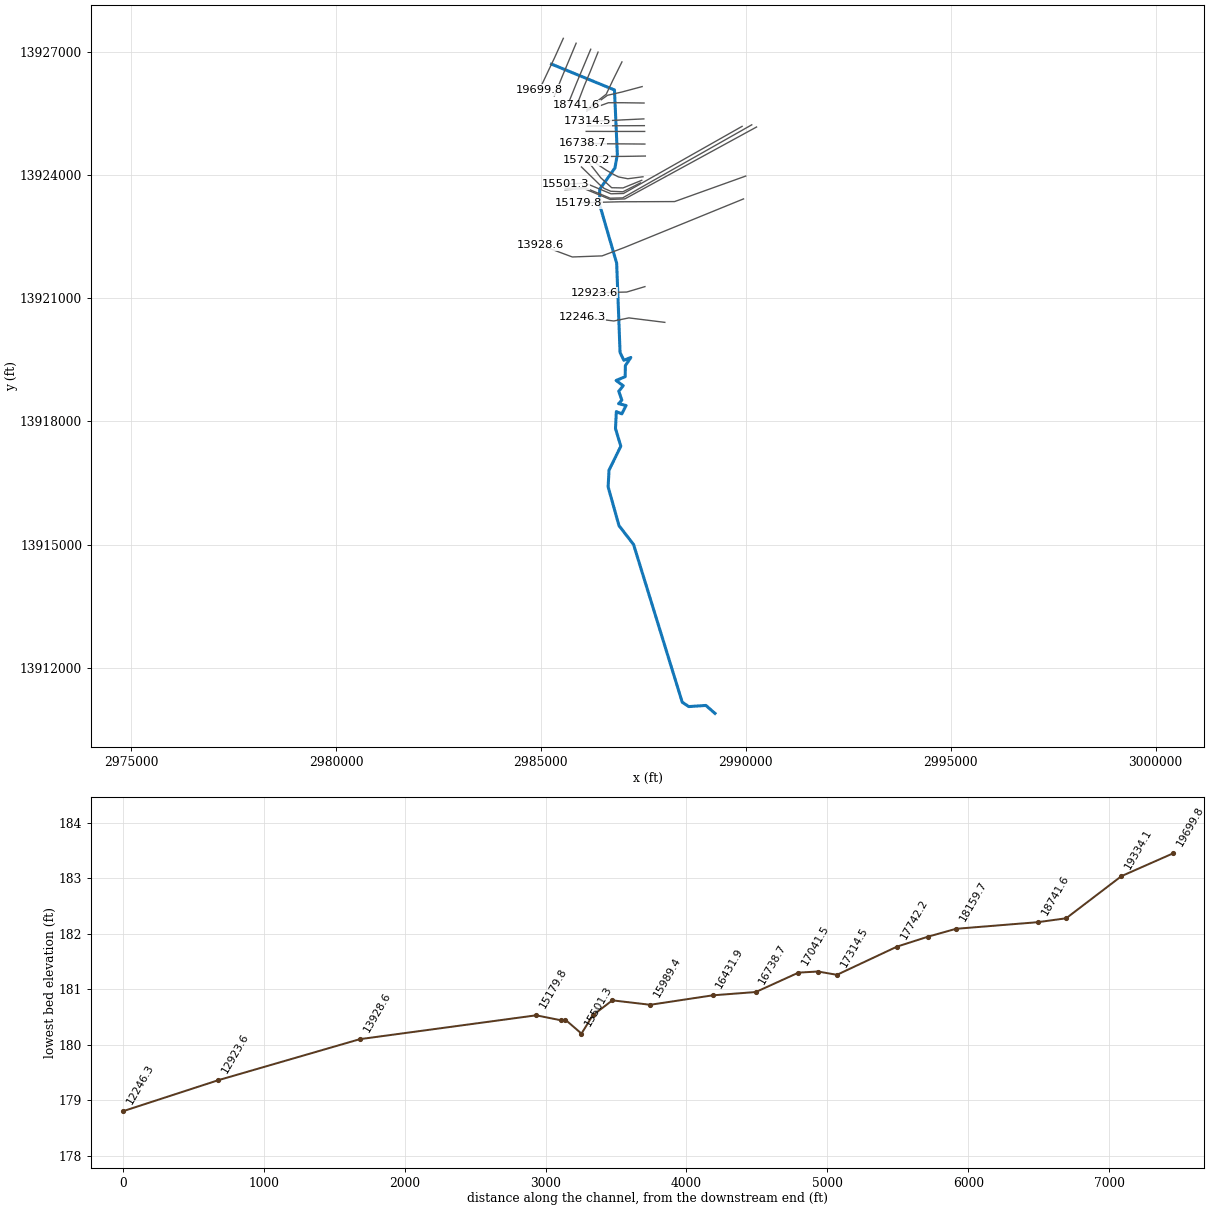
--- K155-00-00.prj (project) ---

Proj Title=K155-00-00
Current Plan=p02
Default Exp/Contr=0.3,0.1
English Units
Geom File=g01
Flow File=f01
Flow File=f02
Plan File=p01
Plan File=p02
Y Axis Title=Elevation
X Axis Title(PF)=Main Channel Distance
X Axis Title(XS)=Station
BEGIN DESCRIPTION:
HCFCD Watershed Unit ID: K
M3 Study Identifier: 2013_Effective_K
Engineer: HCFCD
Project Name: Effective FEMA Study for watershed Cypress Creek (K)
Study Completion Date: [No Data]
FEMA Case Number: 08-06-2369P
FEMA Approval Date: 10/16/2013
Vertical Datum: NAVD 1988
Datum Note: 2001 ADJ
HYDRAULICS
HCFCD Unit No.:  K155-00-00
Hydraulic Program Name: HEC-RAS
Hydraulic Program Version: 3.1.3
Steady Hydraulic Model: Yes
Unsteady Hydraulic Model: No
Update 1:
The effective FEMA hydraulic model for unit number K1550-00-00 has been updated by FEMA LOMR 14-06-1080P with an effective date of 10/10/2014.
END DESCRIPTION:
DSS Export Rating Curves= 0
DSS Export Rating Curve Sorted= 0
DSS Export Volume Flow Curves= 0
DXF OffsetX= 0
DXF OffsetY= 0
DXF ScaleX= 1
DXF ScaleY= 10

--- K155-00-00.p02 (plan) ---

Plan Title=Effective FW 2014
Program Version=3.13
Short Identifier=Eff+LOMR FW
Geom File=g01
Flow File=f02
Subcritical Flow
K Sum by GR= 0
Std Step Tol= 0.01
Critical Tol= 0.01
Num of Std Step Trials= 20
Max Error Tol= 0.3
Flow Tol Ratio= 0.0001
Split Flow NTrial= 30
Split Flow Tol= 0.02
Split Flow Ratio= 0.02
Log Output Level= 0
Friction Slope Method= 1
Unsteady Friction Slope Method= 2
Unsteady Bridges Friction Slope Method= 1
Parabolic Critical Depth
Global Vel Dist= 0 , 0 , 0
Global Log Level= 0
CheckData=True
Encroach Param=-1 ,0,0, 2
Encroach River=K155-00-00
Encroach Reach=K155-00-00_0024
Encroach Node=19699.8
       1 4870.37 5140.46
Encroach Node=19334.1
       1 4859.99 5141.09
Encroach Node=18941.7
       1 4857.74 5137.66
Encroach Node=18741.6
       1 4858.41 5136.18
Encroach Node=18159.7
       1 4856.78  5138.2
Encroach Node=17963.5
       1 4855.71 5139.05
Encroach Node=17742.2
       1 4863.24 5137.43
Encroach Node=17314.5
       1 4870.95 5139.37
Encroach Node=17180.3
       1 4866.43 5136.29
Encroach Node=17041.5
       1 4868.45 5140.05
Encroach Node=16738.7
       1 4870.66 5272.17
Encroach Node=16431.9
       1    4874 5143.13
Encroach Node=15989.4
       1 4845.98 5153.26
Encroach Node=15720.2
       1 4839.83 5159.56
Encroach Node=15581.4
       1 4954.49 5046.14
Encroach Node=15501.3
       1 4940.21 5040.05
Encroach Node=15387.3
       1 4944.31 5049.92
Encroach Node=15356.6
       1 4943.41 5049.02
Encroach Node=15179.8
       1 4946.48 5039.73
Encroach Node=13928.6
       1 4959.51 5045.01
Encroach Node=12923.6
       1 4867.64 4940.03
Encroach Node=12246.3
       1  4975.9 5161.23
Encroach Node=11473
       1    4960    5015
Encroach Node=10212
       1    4963    5071
Encroach Node=8393
       1  4975.2  5057.3
Encroach Node=8239
       1  4980.2  5064.7
Encroach Node=7759
       1  4980.2  5064.7
Encroach Node=7543
       1    4880    5170
Encroach Node=7420
       1    4900    5120
Encroach Node=7318
       1    4940    5040
Encroach Node=6745
       1    4960    5065
Encroach Node=5779
       1    4775    5085
Encroach Node=4562
       1    4635    5015
Encroach Node=3615
       1 4695.23 5197.25
Encroach Node=3515
       1    4720    5200
Encroach Node=3486
       1    4715    5205
Encroach Node=3386
       1 4733.32 5193.84
Encroach Node=2379
       1  4975.7 5368.71
BEGIN DESCRIPTION:
FEMA Effective Floodway October 2013 + LOMR 14-06-1080P
END DESCRIPTION:
Computation Interval=1HOUR
Output Interval=1HOUR
Run HTab= 0
Run UNet= 0
Run PostProcess= 0
UNET Theta= 1
UNET Theta Warmup= 1
UNET ZTol= 0.02
UNET ZSATol= 0.1
UNET MxIter= 20
UNET MaxInSteps= 20
UNET DtIC= 0
UNET DtMin= 0
UNET MaxCRTS= 20
UNET WFStab= 2
UNET SFStab= 1
UNET WFX= 1
UNET SFX= 1
UNET DSS MLevel= 4
UNET DZMax Abort= 100
UNET Convert EG Bridges=-1
UNET Use Existing IB Tables=-1
UNET Froude Reduction=False
UNET Froude Limit= 1
UNET Froude Power= 10
Instantaneous Interval=1HOUR
DSS File=dss
Write IC File= 0
IC Time=0,,
Echo Input=False
Echo Output=False
Write Detailed= 0
Detailed Automatic Start=False, 10

--- K155-00-00.p01 (plan) ---

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Plan Title=Effective MP 2014
Short Identifier=Eff+LOMR MP
Geom File=g01
Flow File=f01
Flow Tol Ratio= 0.001
Encroach Param=-1 ,0,0, 0
FEMA Effective Mult-Profile October 2013 + LOMR 14-06-1080P
UNET ZSATol= 0.05
UNET MaxInSteps= 0

--- K155-00-00.f02 (steady flow) ---

Flow Title=FW
Program Version=3.13
Number of Profiles= 2
Profile Names=1PCT_100yr,100yr_FLOODWAY
River Rch & RM=K155-00-00,K155-00-00_0024 ,19699.8
     389     389
River Rch & RM=K155-00-00,K155-00-00_0024 ,16738.7
     397     397
River Rch & RM=K155-00-00,K155-00-00_0024 ,15387.3
     444     444
River Rch & RM=K155-00-00,K155-00-00_0024 ,13928.6
     451     451
River Rch & RM=K155-00-00,K155-00-00_0024 ,12923.6
     464     464
River Rch & RM=K155-00-00,K155-00-00_0024 ,12246.3
     469     469
River Rch & RM=K155-00-00,K155-00-00_0024 ,11473
     474     474
River Rch & RM=K155-00-00,K155-00-00_0024 ,10212
     482     482
River Rch & RM=K155-00-00,K155-00-00_0024 ,8393
     493     493
River Rch & RM=K155-00-00,K155-00-00_0024 ,7543
     499     499
River Rch & RM=K155-00-00,K155-00-00_0024 ,5779
     532     532
River Rch & RM=K155-00-00,K155-00-00_0024 ,4562
     541     541
River Rch & RM=K155-00-00,K155-00-00_0024 ,3515
     835     835
River Rch & RM=K155-00-00,K155-00-00_0024 ,2379
     963     963
Boundary for River Rch & Prof#=K155-00-00,K155-00-00_0024 , 1
Up Type= 0
Dn Type= 3
Dn Slope=0.002
Boundary for River Rch & Prof#=K155-00-00,K155-00-00_0024 , 2
Up Type= 0
Dn Type= 1
Dn Known WS=155.62
DSS Import GetInterval= 0
DSS Import GetPeak= 0
DSS Import FillOption= 0

--- K155-00-00.f01 (steady flow) ---

Flow Title=MP
Program Version=3.13
Number of Profiles= 4
Profile Names=10PCT_10yr, 2PCT_50yr, 1PCT_100yr, 0.2PCT_500yr
River Rch & RM=K155-00-00,K155-00-00_0024 ,19699.8
     138     289     389     725
River Rch & RM=K155-00-00,K155-00-00_0024 ,16738.7
     141     296     397     740
River Rch & RM=K155-00-00,K155-00-00_0024 ,15387.3
     158     331     444     828
River Rch & RM=K155-00-00,K155-00-00_0024 ,13928.6
     160     336     451     840
River Rch & RM=K155-00-00,K155-00-00_0024 ,12923.6
     165     345     464     865
River Rch & RM=K155-00-00,K155-00-00_0024 ,12246.3
     167     349     469     874
River Rch & RM=K155-00-00,K155-00-00_0024 ,11473
     168     353     474     884
River Rch & RM=K155-00-00,K155-00-00_0024 ,10212
     172     359     482     900
River Rch & RM=K155-00-00,K155-00-00_0024 ,8393
     175     367     493     919
River Rch & RM=K155-00-00,K155-00-00_0024 ,7543
     177     371     499     930
River Rch & RM=K155-00-00,K155-00-00_0024 ,5779
     189     396     532     992
River Rch & RM=K155-00-00,K155-00-00_0024 ,4562
     192     403     541    1009
River Rch & RM=K155-00-00,K155-00-00_0024 ,3515
     297     622     835    1557
River Rch & RM=K155-00-00,K155-00-00_0024 ,2379
     342     717     963    1796
Boundary for River Rch & Prof#=K155-00-00,K155-00-00_0024 , 1
Up Type= 0
Dn Type= 3
Dn Slope=0.002
Boundary for River Rch & Prof#=K155-00-00,K155-00-00_0024 , 2
Up Type= 0
Dn Type= 3
Dn Slope=0.002
Boundary for River Rch & Prof#=K155-00-00,K155-00-00_0024 , 3
Up Type= 0
Dn Type= 3
Dn Slope=0.002
Boundary for River Rch & Prof#=K155-00-00,K155-00-00_0024 , 4
Up Type= 0
Dn Type= 3
Dn Slope=0.002
DSS Import GetInterval= 0
DSS Import GetPeak= 0
DSS Import FillOption= 0

--- K155-00-00.g01 (geometry) ---

Geom Title=K155-00-00
Program Version=3.13

River Reach=K155-00-00      ,K155-00-00_0024
Reach XY= 30
 2985259.907334113926711.3980523 2986795.132468213926080.8909378
 2986864.973194813924507.1171792 2986806.433372413924179.9828775
  2986434.313398 13923660.574026 2986433.539739613923283.7216549
 2986848.187196313921858.4858677      2986931.43     13919682.13
      2987022.91     13919491.04      2987194.08     13919559.86
      2987060.67     13919360.83      2987056.25       13919092.
      2986834.69     13918998.54      2987008.59     13918871.25
      2986899.21     13918737.13      2986974.74     13918519.68
      2986895.31     13918433.75       2987077.6     13918389.48
      2986974.74     13918185.05      2986840.25       13918240.
      2986819.79     13917828.28      2986949.61     13917396.31
      2986662.24     13916813.95      2986640.25       13916406.
        2986905.       13915461.      2987260.75       13915000.
      2988447.95     13911156.91      2988608.03     13911049.92
      2989026.31     13911077.27      2989246.72      13910884.2

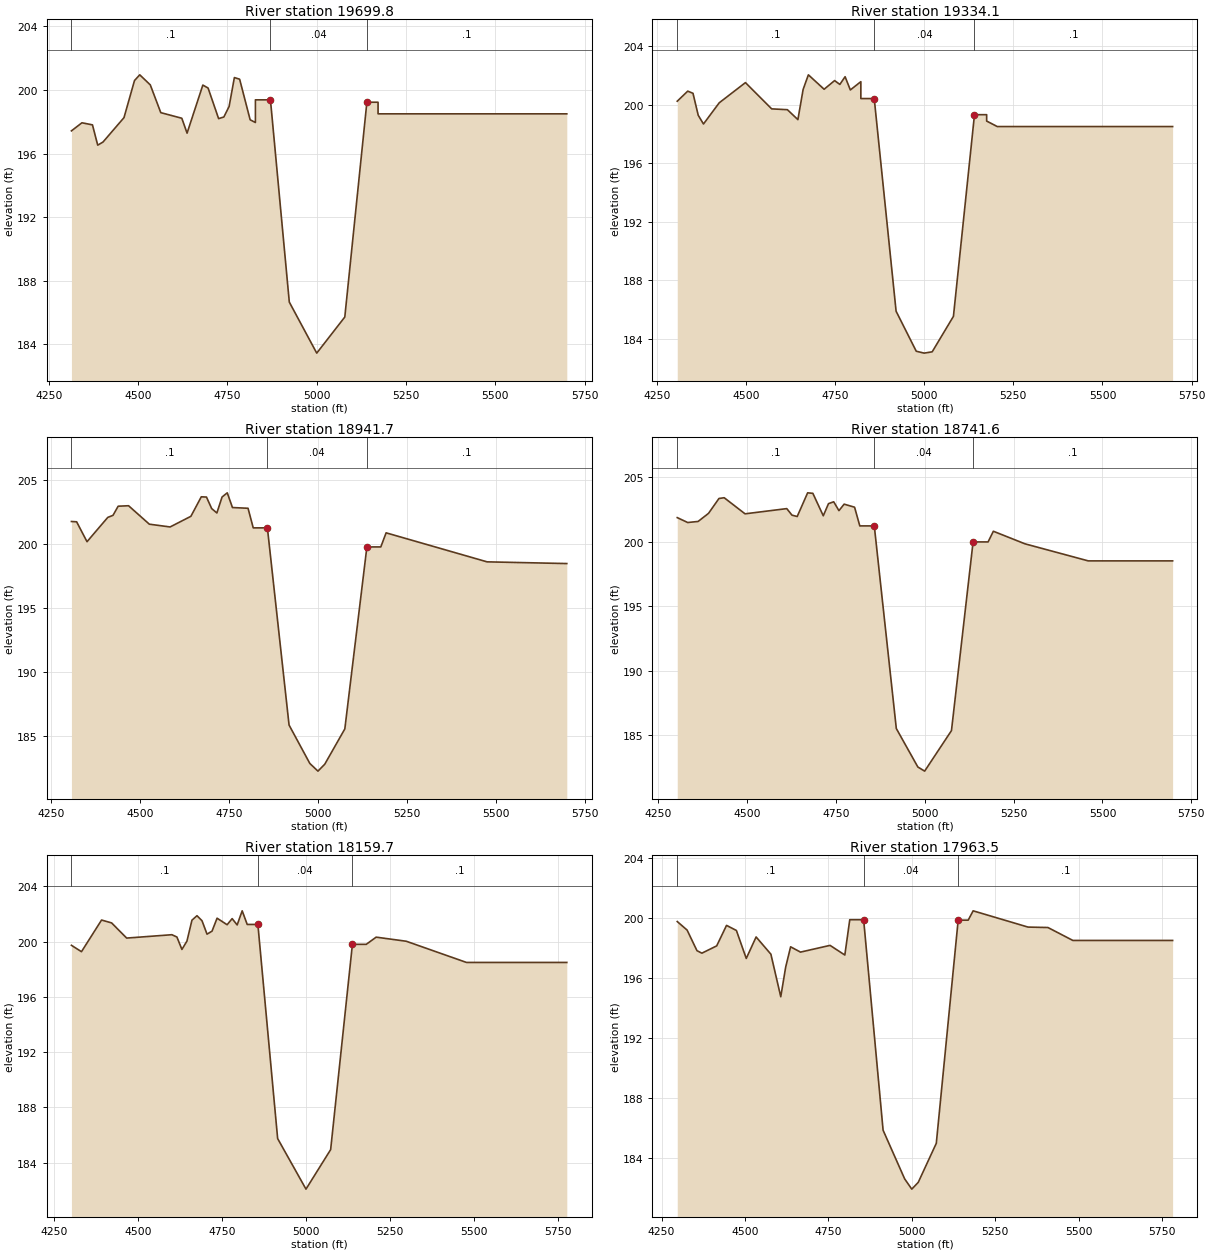
Type RM Length L Ch R = 1 ,19699.8 ,350.85,365.75,363.41
BEGIN DESCRIPTION:
Surveyed Channel XS1
END DESCRIPTION:
XS GIS Cut Line= 4
     2985546.855     13927339.66        2985335.       13926870.
        2985187.       13926560.     2984961.455     13926081.96
#Sta/Elev= 30
 4313.02197.4291 4342.46197.9375 4371.91197.8062 4386.63196.5307 4401.35196.7249
 4460.23198.2611 4489.67 200.596 4504.39200.9538 4533.83200.3215 4563.28198.5741
 4622.16198.2233 4636.88197.2855 4681.04200.3088 4695.76200.1225 4725.21198.1995
 4739.93198.3026 4754.65198.9661 4769.37200.7809 4784.09200.6788 4813.53198.1267
 4828.25197.9543 4828.25  199.38 4870.37  199.38  4923.2  186.66    5000  183.45
 5078.61  185.72 5140.46  199.23 5171.76  199.23 5171.77   198.5 5700.34   198.5
#Mann= 3 , 0 , 0
 4313.02      .1       0 4870.37     .04       0 5140.46      .1       0
#Block Obstruct= 2 , 0
    5000 4828.25  199.38            5000
Bank Sta=4870.37,5140.46
Pilot Channel=183.361,2,0.04
Exp/Cntr=0.3,0.1

Type RM Length L Ch R = 1 ,19334.1 ,384.4,392.41,384.1
BEGIN DESCRIPTION:
Surveyed Channel XS2
END DESCRIPTION:
XS GIS Cut Line= 4
     2985859.373     13927220.75   2985660.8012913926745.8587599
 2985524.139465913926420.6036181     2985328.855     13925937.14
#Sta/Elev= 30
  4307.7200.2298 4337.11200.9173 4351.82200.7698 4366.52199.2691 4381.23198.6748
 4425.35200.1198 4498.88 201.499 4572.42 199.707 4616.54199.6508 4645.95198.9731
 4660.66201.0354 4675.36202.0303 4719.48201.0462  4748.9201.6373  4763.6 201.375
 4778.31201.9009 4793.02200.9988 4822.43201.5625 4822.43  200.41 4859.99  200.41
  4921.3   185.9 4977.78  183.17    5000  183.04 5022.54  183.13 5082.09  185.55
 5141.09  199.31 5175.22  199.31 5175.23198.8752 5205.02   198.5 5696.65   198.5
#Mann= 3 , 0 , 0
  4307.7      .1       0 4859.99     .04       0 5141.09      .1       0
#Block Obstruct= 2 , 0
    5000 4822.43  200.41            5000
Bank Sta=4859.99,5141.09
Pilot Channel=183.241,2,0.04
Exp/Cntr=0.3,0.1

Type RM Length L Ch R = 1 ,18941.7 ,200.39,200.12,199.86
BEGIN DESCRIPTION:
Surveyed Channel XS3
END DESCRIPTION:
XS GIS Cut Line= 4
     2986215.509     13927073.97  2986017.48865113926602.3638444
 2985878.093590913926271.6422296     2985681.602     13925786.64
#Sta/Elev= 30
 4306.41201.7867 4321.02 201.764 4350.25200.2087  4408.7202.1087 4423.32202.2663
 4437.93202.9826 4467.16203.0189 4525.62201.5765 4584.07201.3608 4642.53202.1937
 4671.76203.7169 4686.37203.6967 4700.99202.7968  4715.6202.4531 4730.22203.7015
 4744.83204.0278 4759.44202.8777 4803.29202.8214  4817.9  201.29 4857.74  201.29
 4918.71  185.88 4977.12  182.88    5000  182.28 5019.13  182.82  5075.6  185.58
 5137.66   199.8  5176.8   199.8 5191.75200.9016 5475.83198.6342  5700.1   198.5
#Mann= 3 , 0 , 0
 4306.41      .1       0 4857.74     .04       0 5137.66      .1       0
#Block Obstruct= 2 , 0
    5000  4817.9  201.29            5000
Bank Sta=4857.74,5137.66
Pilot Channel=183.191,2,0.04
Exp/Cntr=0.3,0.1

Type RM Length L Ch R = 1 ,18741.6 ,588.11,581.9,575.89
BEGIN DESCRIPTION:
Surveyed Channel XS4
END DESCRIPTION:
XS GIS Cut Line= 4
     2986394.381     13927003.51  2986203.34873313926527.1998369
 2986062.587054313926195.1116038     2985876.735     13925710.75
#Sta/Elev= 30
 4304.48201.8527 4333.81201.4731 4363.13201.5555 4392.46202.1848 4421.78203.3359
 4436.44203.3934 4495.09202.1461  4612.4202.5501 4627.06202.0426 4641.72 201.938
 4671.04203.7735 4685.71203.7346 4715.03201.9944 4729.69202.9351 4744.36203.0786
 4759.02202.3923 4773.68202.8954 4803.01202.6592 4817.67  201.21 4858.41  201.21
 4920.35  185.51 4980.89  182.53    5000  182.21 5075.41  185.35 5136.18  199.97
 5178.36  199.97 5193.18200.7963 5282.12199.8212 5459.99   198.5 5697.15   198.5
#Mann= 3 , 0 , 0
 4304.48      .1       0 4858.41     .04       0 5136.18      .1       0
#Block Obstruct= 2 , 0
    5000 4817.67  201.21            5000
Bank Sta=4858.41,5136.18
Pilot Channel=182.741,2,0.04
Exp/Cntr=0.3,0.1

Type RM Length L Ch R = 1 ,18159.7 ,325.72,196.16,71.59
BEGIN DESCRIPTION:
Surveyed Channel XS5
END DESCRIPTION:
XS GIS Cut Line= 5
     2986977.071     13926765.01  2986744.52955313926296.2413439
 2986740.429698513926285.3083979 2986592.8349282 13925976.452675
     2986120.652     13925610.47
#Sta/Elev= 30
 4301.76199.7394 4331.66199.2781 4391.47201.5689 4421.37201.3612 4466.22200.2628
 4600.78200.5067 4615.73200.3398 4630.68199.4413 4645.63 200.045 4660.58201.5594
 4675.53201.8822 4690.48201.5176 4705.43200.5465 4720.38200.7662 4735.33201.7031
 4765.24 201.228 4780.19201.6716 4795.14201.2145 4810.09 202.236 4825.04  201.25
 4856.78  201.25 4915.64  185.75    5000  182.09 5073.43  184.95  5138.2  199.81
 5179.42  199.81  5208.9200.3305 5298.51 200.034 5477.73   198.5 5776.44   198.5
#Mann= 3 , 0 , 0
 4301.76      .1       0 4856.78     .04       0  5138.2      .1       0
#Block Obstruct= 2 , 0
    5000 4825.04  201.25            5000
Bank Sta=4856.78,5138.2
Pilot Channel=182.741,2,0.04
Exp/Cntr=0.3,0.1

Type RM Length L Ch R = 1 ,17963.5 ,252.06,221.32,190.94
BEGIN DESCRIPTION:
Surveyed Channel XS6
END DESCRIPTION:
XS GIS Cut Line= 4
     2987470.324     13926163.35  2986970.77951113926030.0212092
 2986624.718117713925951.4915485     2986125.988     13925595.48
#Sta/Elev= 30
 4297.13199.7583 4326.67199.1901 4356.22  197.82 4370.99197.6533 4415.31 198.139
 4444.85199.5029  4474.4199.1638 4503.94197.3022 4533.49198.7325  4577.8197.5847
 4607.35194.7534 4622.12196.7291 4636.89198.0772 4666.44197.7242 4755.07198.1728
 4799.39197.5306 4814.16  199.88 4855.71  199.88 4914.06  185.87 4978.72  182.63
    5000  181.95 5019.39   182.4 5073.52     185 5139.05  199.85 5169.02  199.85
 5183.96200.4719 5348.36199.3898 5408.15199.3605 5482.87   198.5 5781.78   198.5
#Mann= 3 , 0 , 0
 4297.13      .1       0 4855.71     .04       0 5139.05      .1       0
#Block Obstruct= 2 , 0
    5000 4814.16  199.88            5000
Bank Sta=4855.71,5139.05
Pilot Channel=182.383,2,0.04
Exp/Cntr=0.3,0.1

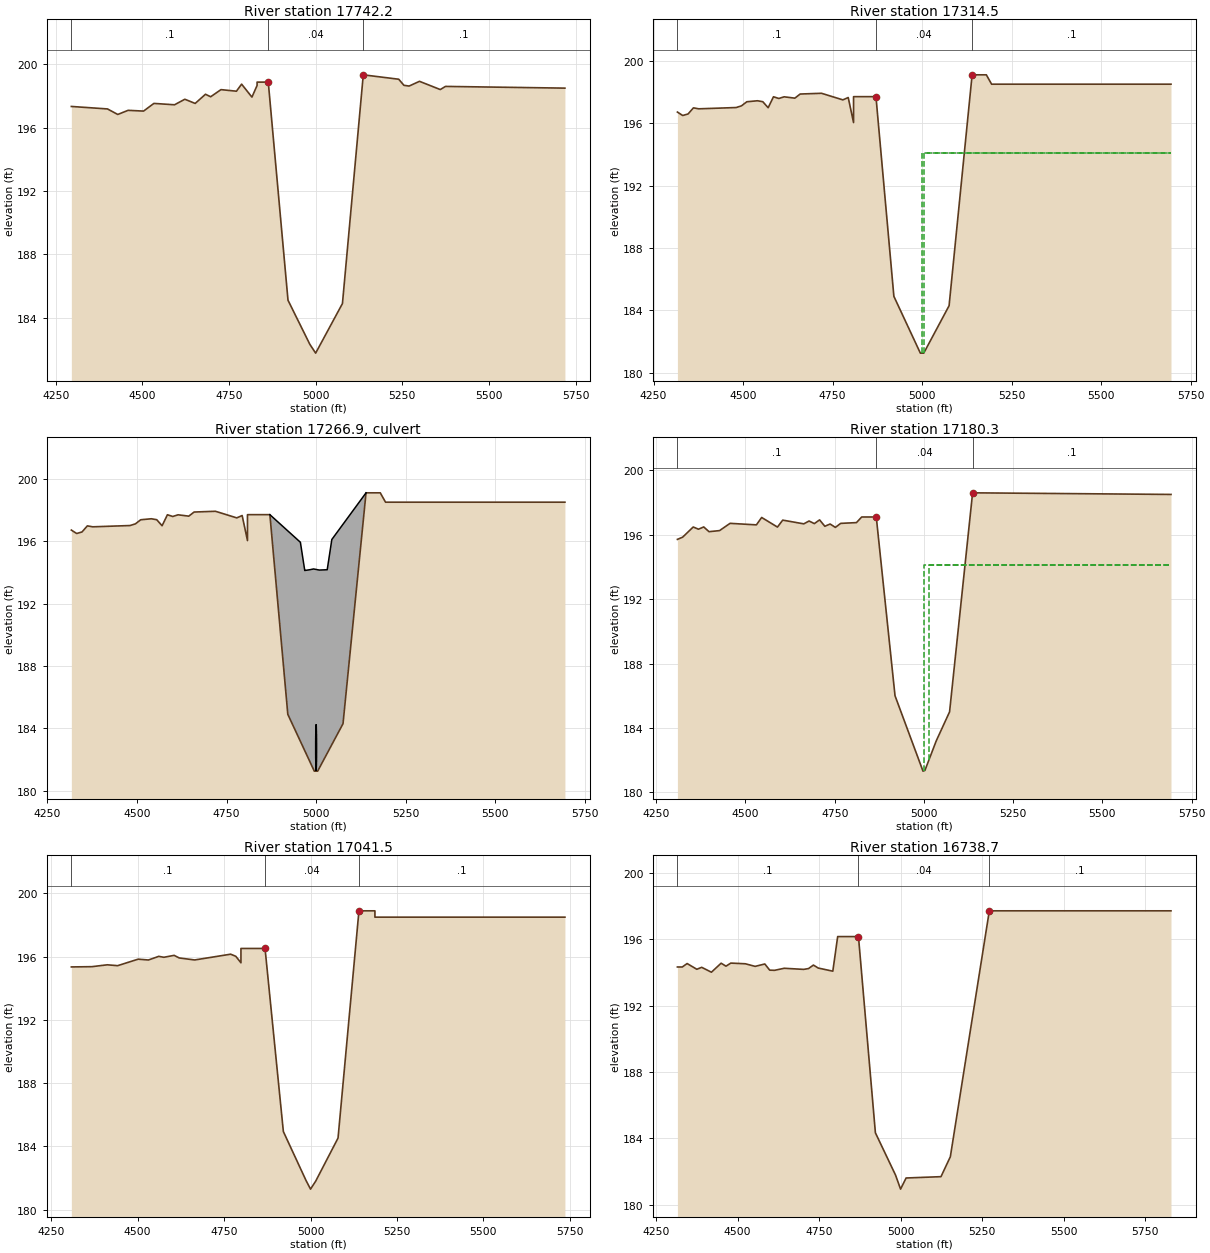
Type RM Length L Ch R = 1 ,17742.2 ,427.57,427.72,427.71
BEGIN DESCRIPTION:
Surveyed Channel XS7
END DESCRIPTION:
XS GIS Cut Line= 6
     2987516.905     13925762.75  2986980.919921       13925770.
        2986945.       13925770.        2986691.       13925770.
 2986647.0800781       13925770.     2986125.988     13925580.24
#Sta/Elev= 30
 4294.94197.3434 4399.17197.1866 4428.94196.8383 4458.72197.0978 4503.39 197.051
 4533.17197.5353 4592.73 197.449 4622.51197.7987 4652.29197.5334 4682.07198.1133
 4696.96197.9549 4726.74198.4054 4771.41198.3059  4786.3198.7516 4816.08197.9334
 4830.97198.6663 4830.97  198.88 4863.24  198.88  4920.2  185.11 4983.14  182.33
    5000  181.77 5077.32   184.9 5137.43  199.34 5239.75 199.062 5254.74198.6781
 5269.73 198.631 5299.71198.9297 5359.66198.4096 5374.65198.6086 5719.38   198.5
#Mann= 3 , 0 , 0
 4294.94      .1       0 4863.24     .04       0 5137.43      .1       0
#Block Obstruct= 2 , 0
    5000 4830.97  198.88            5000
Bank Sta=4863.24,5137.43
Pilot Channel=181.93,2,0.04
Exp/Cntr=0.5,0.3

Type RM Length L Ch R = 1 ,17314.5 ,134.19,134.14,134.15
BEGIN DESCRIPTION:
Surveyed Channel XS8
END DESCRIPTION:
XS GIS Cut Line= 4
     2987511.739     13925375.96     2987020.575     13925352.94
     2986650.481     13925333.04     2986135.135     13925321.08
#Sta/Elev= 30
 4316.73196.7122 4331.63196.4923 4346.53196.5919 4361.43196.9823 4376.33 196.921
 4480.63197.0029 4495.53197.1107 4510.43 197.373 4540.23197.4371 4555.13 197.376
 4570.03196.9902 4584.93197.6934 4599.83197.5832 4614.73197.6909 4644.53197.6042
 4659.43197.8689 4719.03197.9165 4778.63197.4935 4793.53197.6451 4808.43196.0387
 4808.43   197.7 4870.95   197.7 4920.99   184.9 4994.91  181.26 5004.41  181.26
 5075.11   184.3 5139.37   199.1 5179.07   199.1 5193.79   198.5 5694.54   198.5
#Mann= 3 , 0 , 0
 4316.73      .1       0 4870.95     .04       0 5139.37      .1       0
#XS Ineff= 2 , 0
    5000  4995.5  194.12  5004.5    5000  194.12
Permanent Ineff=
       F       F
#Block Obstruct= 2 , 0
    5000 4808.43   197.7            5000
Bank Sta=4870.95,5139.37
Pilot Channel=182.18,2,0.04
Exp/Cntr=0.5,0.3

Type RM Length L Ch R = 2 ,17266.9 ,,,
BEGIN DESCRIPTION:
Control Structure No.2
END DESCRIPTION:
Bridge Culvert--1,0,-1,-1, 0
Deck Dist Width WeirC Skew NumUp NumDn MinLoCord MaxHiCord MaxSubmerge Is_Ogee
47.59,36.81,2.6,0, 16, 15, 194.12, , 0.95, 0, 4,4,,
 4870.95 4956.14 4966.82 4968.05  4968.3 4984.57 4992.72 4992.96 4993.01 5008.77
 5009.15 5030.81 5030.95 5031.31 5043.87 5139.37
   197.7  195.93  194.34  194.16  194.12  194.18  194.22  194.22  194.22  194.15
  194.15  194.17  194.17  194.22  196.11   199.1
                                                                                
                                                
 4866.43 4956.584970.685 4972.684995.9144995.9144995.9254996.7455013.1045013.851
5023.518 5029.895030.0425043.433 5136.29
   197.1 195.913  194.13 194.139 194.146 194.146 194.146 194.144 194.113 194.112
 194.108 194.107  194.13 196.186   198.6
                                                                                
                                        
BR Coef=-1 , 0 , 0 ,, 0 ,,,0.8,-1,,0,
WSPro=,,,, 1 ,,,, 0 ,,,, 0 ,,,,-1 ,-1 ,-1 , 0 , 0 , 0 , 0 , 0
Culvert=1,3,,120.63,0.013,0.5,1,1,1,181.26,5000,181.35,5000,Culvert #1  , 0 ,1
Culvert Bottom n=0.013
BC Design=,, 0 ,, 0 ,,,,,,
BC HTab HWMax=199.5
BC HTab TWMax=199
BC HTab MaxFlow=1500

Type RM Length L Ch R = 1 ,17180.3 ,145.05,138.78,138.72
BEGIN DESCRIPTION:
Surveyed Channel XS9
END DESCRIPTION:
XS GIS Cut Line= 4
     2987523.935     13925211.31     2987007.629     13925208.89
     2986645.536     13925208.25     2986141.233     13925199.12
#Sta/Elev= 30
 4309.32 195.709 4324.07195.8481 4353.57196.4783 4368.33196.3411 4383.08196.4813
 4397.83196.1878 4427.33 196.254 4456.84 196.705  4530.6196.6107 4545.35197.0697
  4589.6196.4735 4604.35196.9044 4663.36196.6738 4678.11196.8503 4692.87196.6888
 4707.62196.9196 4722.37196.5223 4737.12196.6634 4751.87 196.454 4766.62196.7035
 4810.88196.7507 4825.63   197.1 4866.43   197.1 4918.98     186 4997.31  181.32
 5002.69  181.36 5034.46   183.2 5071.79     185 5136.29   198.6 5692.11   198.5
#Mann= 3 , 0 , 0
 4309.32      .1       0 4866.43     .04       0 5136.29      .1       0
#XS Ineff= 2 , 0
    5000    4986  194.11    5014    5000  194.11
Permanent Ineff=
       F       F
#Block Obstruct= 2 , 0
    5000 4825.63   197.1            5000
Bank Sta=4866.43,5136.29
Pilot Channel=181.93,2,0.04
Exp/Cntr=0.5,0.3

Type RM Length L Ch R = 1 ,17041.5 ,303.43,302.81,301.85
BEGIN DESCRIPTION:
Surveyed Channel XS10
END DESCRIPTION:
XS GIS Cut Line= 4
      2987532.26       13925070.       2987041.7       13925070.
      2986654.28       13925070.     2986104.704     13925071.54
#Sta/Elev= 25
 4308.21195.3522 4367.67195.3681 4412.27195.4864    4442195.4307 4501.46195.8428
 4531.19195.7903 4560.92196.0211 4575.79195.9626 4605.52196.0836 4620.38195.9188
 4664.98195.7928 4769.04196.1579  4783.9196.0224 4798.77195.6135 4798.77  196.52
 4868.45  196.52 4921.42  184.94 4986.91  181.85    5000   181.3 5014.83   181.8
 5079.56  184.53 5140.05   198.9 5186.19   198.9 5186.19   198.5 5735.77   198.5
#Mann= 3 , 0 , 0
 4308.21      .1       0 4868.45     .04       0 5140.05      .1       0
#Block Obstruct= 2 , 0
    5000 4798.77  196.52            5000
Bank Sta=4868.45,5140.05
Pilot Channel=181.93,2,0.04
Exp/Cntr=0.3,0.1

Type RM Length L Ch R = 1 ,16738.7 ,305.14,306.84,362.27
BEGIN DESCRIPTION:
Surveyed Channel XS11
END DESCRIPTION:
XS GIS Cut Line= 6
      2987536.89     13924762.55     2987045.207     13924766.34
     2986561.622     13924769.21     2986546.622     13924769.28
     2986541.622     13924769.31      2986022.82     13924784.18
#Sta/Elev= 30
 4315.21194.3203 4330.11194.3199 4345.01194.5263 4374.81194.1822 4389.71194.2998
 4419.51194.0058 4449.31194.5474 4464.21 194.369 4479.11194.5543 4523.81194.5125
 4553.61194.3571 4583.41194.5005 4598.31194.1303 4613.21194.1184 4643.01194.2429
 4702.61194.1754 4717.51194.2254 4732.41 194.435 4747.31194.2559 4792.01194.0675
 4806.91  196.15 4870.66  196.15 4922.64  184.34  4984.3   181.8  4999.9  180.95
 5016.82  181.62 5123.85   181.7 5152.58   182.9 5272.17   197.7 5829.52   197.7
#Mann= 3 , 0 , 0
 4315.21      .1       0 4870.66     .04       0 5272.17      .1       0
#Block Obstruct= 2 , 0
    5000 4806.91  196.15            5000
Bank Sta=4870.66,5272.17
Pilot Channel=179.125,2,0.04
Exp/Cntr=0.3,0.1

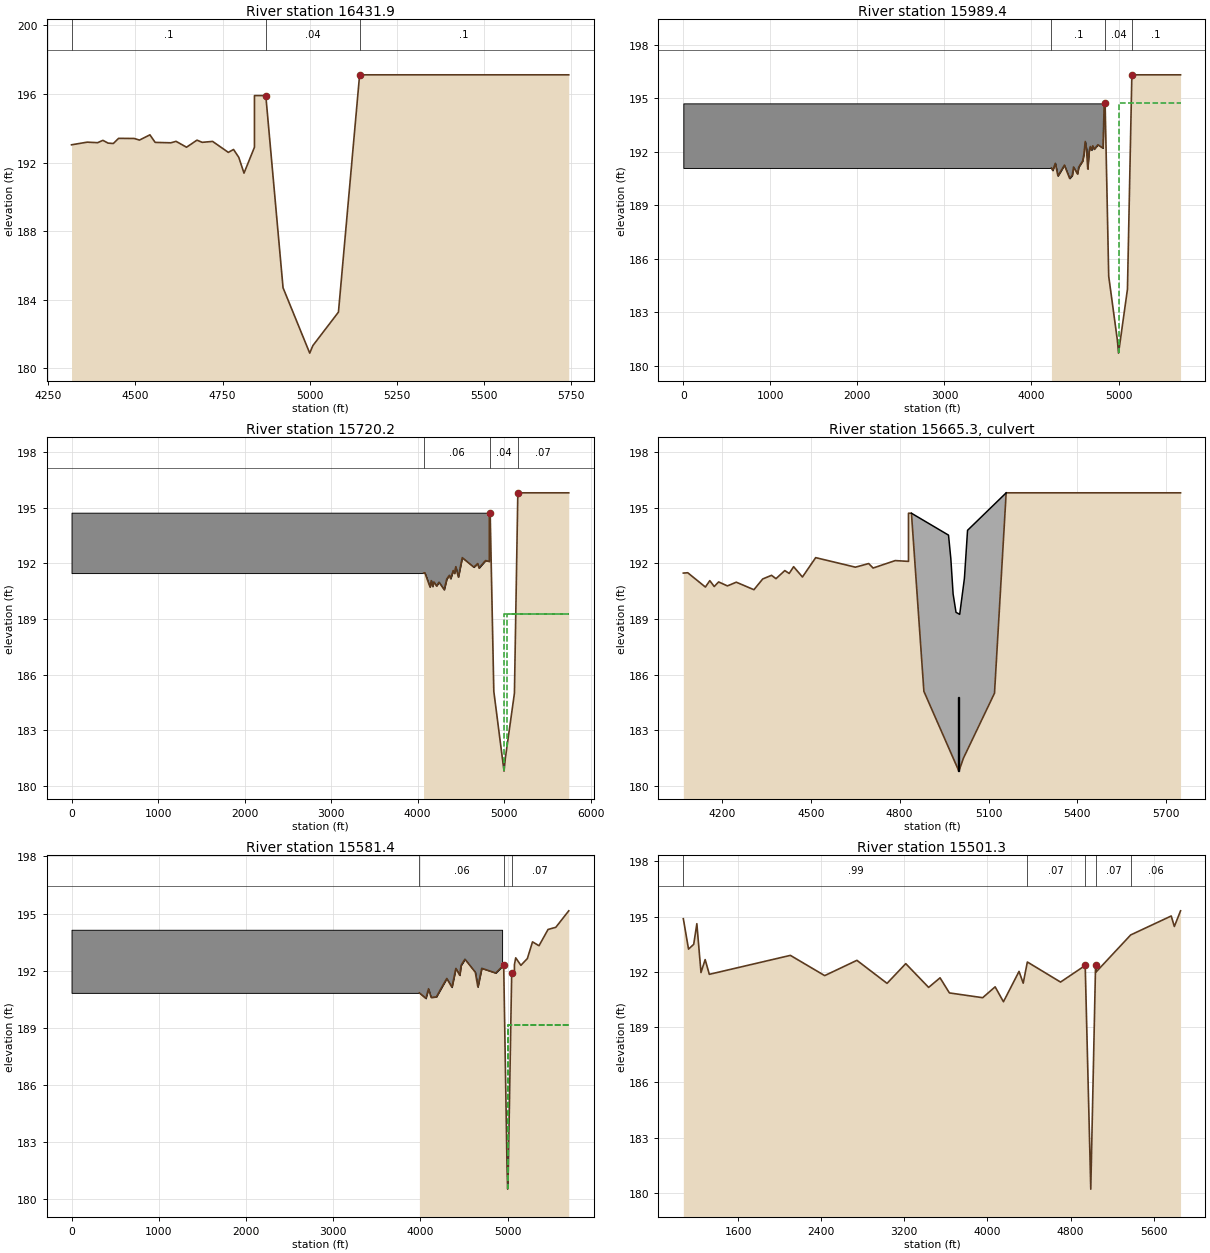
Type RM Length L Ch R = 1 ,16431.9 ,513.95,442.45,365.7
BEGIN DESCRIPTION:
Surveyed Channel XS13
END DESCRIPTION:
XS GIS Cut Line= 5
     2987547.712     13924470.55  2987023.12483313924461.8631998
 2986785.623796813924460.9391829  2986693.731054  13924460.25464
     2986121.698     13924458.19
#Sta/Elev= 30
 4316.84193.0315 4361.81193.1861 4391.79193.1555 4406.78193.2913 4421.77  193.13
 4436.76193.1082 4451.75 193.407 4496.72193.4005 4511.71193.3065 4541.69193.6118
 4556.69193.1727 4601.66193.1482 4616.65193.2339 4646.63192.8907 4676.61193.3029
  4691.6 193.176 4721.58193.2283 4766.55192.5904 4781.54192.7591 4796.53 192.301
 4811.52191.3802  4841.5192.8893  4841.5   195.9    4874   195.9 4923.51   184.7
    5000  180.89 5009.07  181.33 5082.41  183.28 5143.13  197.11 5742.93  197.11
#Mann= 3 , 0 , 0
 4316.84      .1       0    4874     .04       0 5143.13      .1       0
#Block Obstruct= 2 , 0
    5000  4841.5   195.9            5000
Bank Sta=4874,5143.13
Pilot Channel=178.967,2,0.04
Exp/Cntr=0.3,0.1

Type RM Length L Ch R = 1 ,15989.4 ,305.76,269.21,232.72
BEGIN DESCRIPTION:
Surveyed Channel XS14
END DESCRIPTION:
XS GIS Cut Line= 6
     2987490.548     13923965.34     2987120.087     13923916.87
  2986891.24112213923961.4304621     2986785.624     13924015.68
     2986595.264     13924125.54     2986146.418     13924422.65
#Sta/Elev= 30
 4229.11191.1007 4244.05190.9615 4273.94191.3611 4303.83 190.653 4378.55191.2578
 4438.33190.5123 4468.22190.6798 4483.17191.1546    4528190.7661 4542.95191.1497
 4587.78191.4921 4602.73191.8849 4617.29192.5847 4631.87192.1606 4646.44191.0437
 4661.01192.0069 4675.58192.3025 4690.15192.0959 4704.72192.3424 4719.29192.1472
    4763192.4002 4821.28192.2116 4835.85  194.72 4845.98  194.72 4887.33  185.03
 4986.58  181.45    5000  180.72 5102.69   184.3 5153.26  196.32 5712.71  196.32
#Mann= 3 , 0 , 0
 4229.11      .1       0 4845.98     .04       0 5153.26      .1       0
#XS Ineff= 2 , 0
    5000 4845.98  194.72            5000
Permanent Ineff=
       F       F
#Block Obstruct= 2 , 0
       0 4835.75  194.72               0
Bank Sta=4845.98,5153.26
Pilot Channel=178.745,2,0.04
Exp/Cntr=0.5,0.3

Type RM Length L Ch R = 1 ,15720.2 ,138.83,138.83,138.83
BEGIN DESCRIPTION:
Surveyed Channel XS15
END DESCRIPTION:
XS GIS Cut Line= 6
     2987459.649     13923878.82     2987004.698     13923693.24
  2986736.16867413923697.7815036     2986726.227     13923698.89
        2986461.       13923940.     2986122.567     13924373.33
#Sta/Elev= 30
 4069.92191.4747 4084.81191.4919 4144.37190.7217 4159.26191.0671 4174.15190.7507
 4189.04 190.997 4218.81190.7827 4248.59190.9836 4308.15190.5781 4337.93191.1585
 4367.71191.3537  4382.6191.1731 4412.38191.6091 4427.26191.4548 4442.15191.8194
 4471.93 191.263  4516.6192.3064 4650.79 191.793 4695.55191.9878 4710.47191.7468
 4785.07192.1478 4829.83192.1048 4829.83   194.7 4839.83   194.7 4881.82   185.1
    5000   180.8 5015.41   181.5 5120.19     185 5159.56   195.8 5748.11   195.8
#Mann= 3 , 0 , 0
 4069.92     .06       0 4839.83     .04       0 5159.56     .07       0
#XS Ineff= 2 , 0
    5000 4966.32  189.25 5033.68    5000  189.25
Permanent Ineff=
       F       F
#Block Obstruct= 2 , 0
       0 4829.83  194.73               0
Bank Sta=4839.83,5159.56
Exp/Cntr=0.5,0.3

Type RM Length L Ch R = 2 ,15665.3 ,,,
BEGIN DESCRIPTION:
CULVERT AT DIRT RD 3750' D/S HWY 290
Structure ID: K155-00-00-S02
END DESCRIPTION:
Bridge Culvert--1,0,-1,-1, 0
Deck Dist Width WeirC Skew NumUp NumDn MinLoCord MaxHiCord MaxSubmerge Is_Ogee
54.9,61.92,2.6,0, 9, 10, , , 0.95, 0, 4,4,,
 4839.83    4965  4972.8 4980.47 4990.26 5002.67 5018.59 5029.18 5159.56
   194.7  193.52  192.25  190.35  189.36  189.25  191.19  193.78   195.8
                                                                        
 4936.01    4969 4976.97 4985.51 4988.91 5000.28 5013.72 5019.68    5033 5077.36
  194.15  194.15  192.12   189.8   189.6  189.12  189.61  190.22  194.07  194.07
                                                                                
BR Coef= 1 , 1 , 0 ,1.25, 0 ,,,0.8,0,2,0,
WSPro=,,,, 1 ,,,, 0 ,,,, 0 ,,,,-1 ,-1 ,-1 , 0 , 0 , 0 , 0 , 0
Culvert=2,4,4,100.92,0.013,0.5,1,8,2,180.82,5000,180.6,5000,Culvert #1  , 0 ,31.73
Culvert Bottom n=0.013
BC Design=,, 0 ,, 0 ,,,,,,
BC HTab HWMax=195
BC HTab TWMax=192
BC HTab MaxFlow=1000

Type RM Length L Ch R = 1 ,15581.4 ,64.61,80.05,93.53
BEGIN DESCRIPTION:
DS of Control Structure No. 1 XS16
END DESCRIPTION:
XS GIS Cut Line= 6
     2987427.637     13923814.75     2987001.021     13923599.18
     2986704.989     13923611.74        2986545.       13923680.
        2986436.       13923770.      2985989.25     13924203.94
#Sta/Elev= 30
 3987.78190.8358 4062.47 190.546 4092.34191.0532 4122.21190.5984 4181.96190.6207
 4301.46191.5932 4361.21191.1315 4406.02192.1223 4450.83191.7584 4465.77 192.277
 4510.22192.6035 4628.73 191.922 4658.37191.1452 4702.81192.1263 4863.54191.8806
 4954.49   192.3 4993.04   181.6    5000  180.53 5006.96   181.5 5046.14   191.9
 5077.36   191.9 5077.36192.3162 5092.19192.6762 5151.51 192.282 5225.65192.6382
 5284.97193.5146 5359.11193.3121 5462.91 194.166 5551.88194.2791 5700.17195.1443
#Mann= 3 , 0 , 0
 3987.78     .06       0 4954.49    .013       0 5046.14     .07       0
#XS Ineff= 2 , 0
    5000 4991.64  189.13 5008.36    5000  189.13
Permanent Ineff=
       F       F
#Block Obstruct= 2 , 0
       0 4936.01  194.15 5077.36       0  194.07
Bank Sta=4954.49,5046.14
Exp/Cntr=0.5,0.3

Type RM Length L Ch R = 1 ,15501.3 ,131.72,114.04,102.75
BEGIN DESCRIPTION:
k155-00-00-s2a_private road u/s - XS4-Modified XS17
END DESCRIPTION:
XS GIS Cut Line= 5
      2989908.65       13925194.      2987015.58     13923557.95
      2986710.11     13923549.92      2986087.05     13923809.54
      2985607.93      13923786.3
#Sta/Elev= 30
  1073.7  194.89  1123.7  193.24  1173.7   193.5  1203.7  194.62  1243.7  191.97
  1283.7  192.67  1323.7  191.87  2103.7   192.9  2433.7   191.8  2743.7  192.63
  3033.7  191.38  3213.7  192.45  3433.7  191.16  3543.7  191.68  3633.7  190.86
  3953.7   190.6  4073.7  191.19  4153.7  190.38  4303.7  192.03  4343.7  191.39
  4383.7  192.54  4702.9  191.45 4940.21  192.35 4993.85   180.2 5040.05   192.4
  5045.5     192  5377.9  194.01  5767.9  195.04  5797.9  194.47  5857.6  195.32
#Mann= 5 ,-1 , 0
  1073.7     .99       0  4383.7     .07       0 4940.21     .04       0
  5045.5     .07       0  5377.9     .06       0
Bank Sta=4940.21,5040.05
Exp/Cntr=0.3,0.1

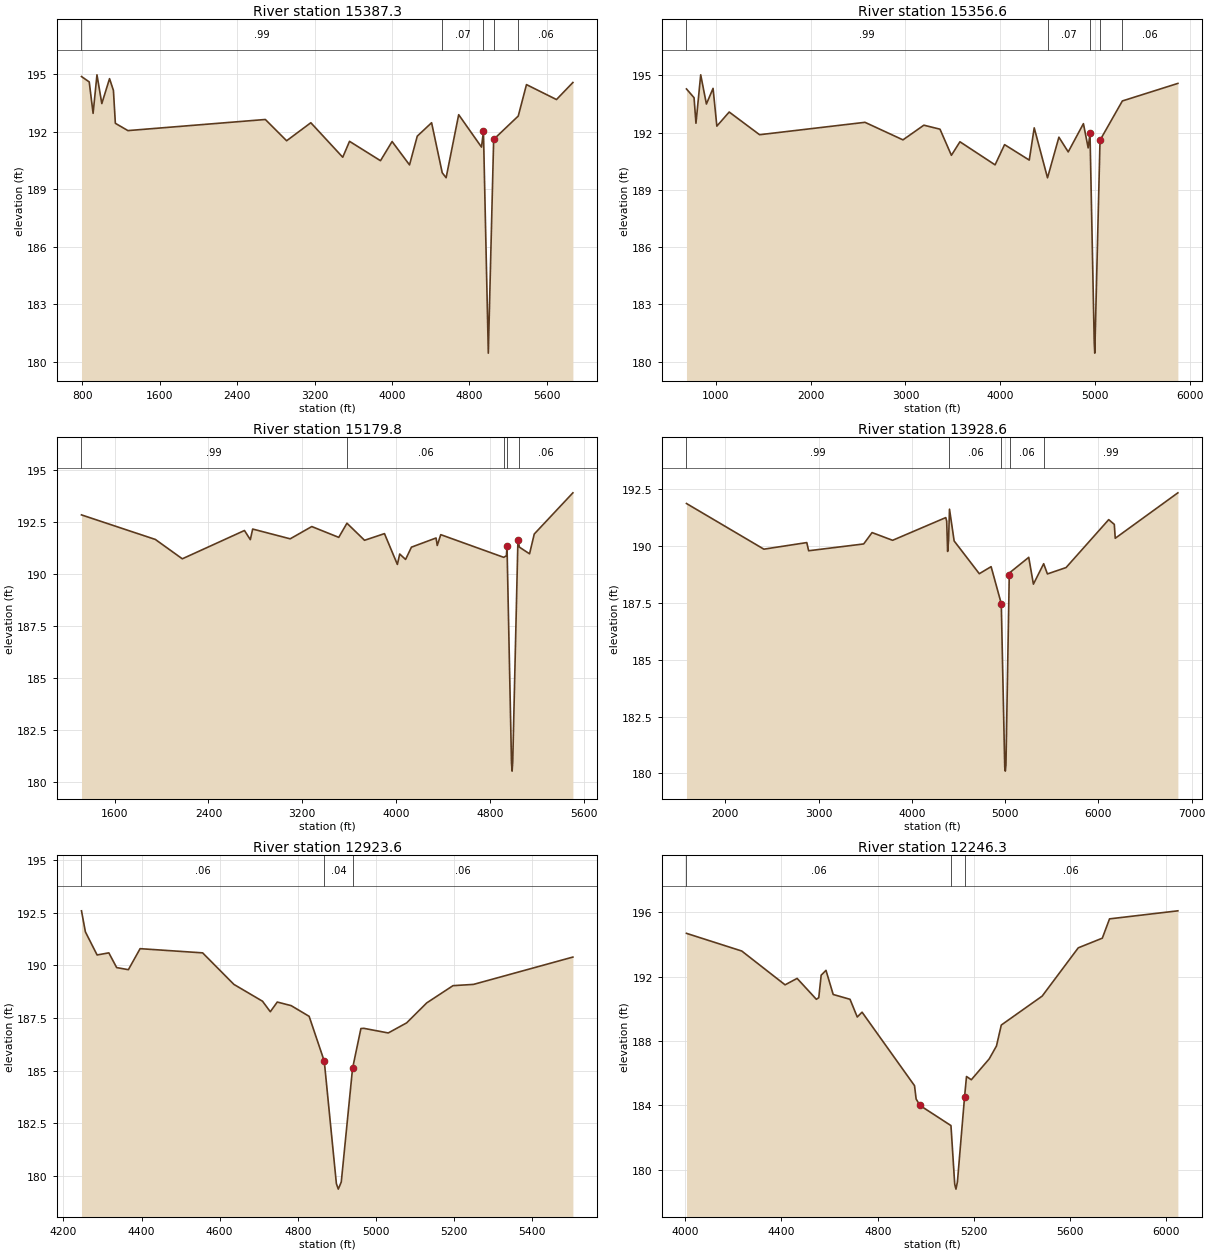
Type RM Length L Ch R = 1 ,15387.3 ,30,30.69,30
BEGIN DESCRIPTION:
k155-00-00-s2a_private road u/s - XS3 (Culvert Removed) updated with Survey XS 18
END DESCRIPTION:
XS GIS Cut Line= 5
      2990144.54     13925231.53      2986995.17     13923450.51
       2986689.7     13923442.48      2986066.63     13923702.09
      2985587.51     13923678.86
#Sta/Elev= 30
   790.4  194.88   870.4   194.6   910.4  192.96   950.4  194.97  1000.4  193.47
  1080.4  194.77  1120.4  194.16  1140.4  192.44  1270.4  192.06  2690.4  192.64
  2910.4  191.53  3160.4  192.47  3490.4  190.67  3560.4   191.5  3880.4  190.49
  4000.4  191.49  4180.4  190.27  4260.4  191.77  4408.5  192.47  4518.5  189.86
  4558.5   189.6  4688.5  192.89  4924.2   191.2 4944.31  192.02 4994.68  180.45
 5049.92   191.6  5304.1  192.82  5389.1  194.46  5699.1  193.68  5868.7  194.57
#Mann= 5 ,-1 , 0
   790.4     .99       0  4518.5     .07       0 4944.31     .04       0
 5049.92     .07       0  5304.1     .06       0
Bank Sta=4944.31,5049.92
Exp/Cntr=0.3,0.1

Type RM Length L Ch R = 1 ,15356.6 ,180,176.82,180
BEGIN DESCRIPTION:
k155-00-00-s2a_private road d/s - XS2 Updated with Survey XS19
END DESCRIPTION:
XS GIS Cut Line= 5
      2990261.56     13925178.34      2987046.43     13923424.88
      2986688.52     13923412.32      2986062.03     13923673.36
      2985586.61     13923650.31
#Sta/Elev= 30
   693.8  194.29   773.8  193.83   793.8  192.49   843.8  195.03   903.8   193.5
   973.8  194.32  1013.8  192.34  1143.8  193.08  1463.8  191.89  2573.8  192.54
  2973.8  191.62  3193.8  192.39  3363.8  192.18  3483.8  190.81  3573.8  191.52
  3943.8  190.31  4043.8  191.37  4303.8  190.56    4356  192.25    4496  189.63
    4616  191.76  4714.1  190.99  4874.1  192.47  4924.2   191.2 4943.41  191.96
 4988.04     181 4993.78  180.44 5049.02   191.6  5284.1  193.66  5868.8  194.58
#Mann= 5 ,-1 , 0
   693.8     .99       0    4496     .07       0 4943.41     .04       0
 5049.02     .07       0  5284.1     .06       0
Bank Sta=4943.41,5049.02
Exp/Cntr=0.3,0.1

Type RM Length L Ch R = 1 ,15179.8 ,1250,1251.22,1283.2
BEGIN DESCRIPTION:
Channel Improvements, B/W 6', Side Slopes 4:1 XS20
END DESCRIPTION:
XS GIS Cut Line= 5
      2989997.74      13923982.3      2988261.55     13923360.42
      2986934.14     13923355.57      2985974.97     13923330.92
      2985915.11     13923325.79
#Sta/Elev= 30
  1317.2  192.84  1947.2  191.66  2177.2  190.73  2707.2  192.09  2757.2  191.65
  2777.2  192.16  3097.2  191.69  3281.4  192.28  3511.4  191.76  3581.4  192.44
  3731.4  191.62  3901.4  191.94  4011.4  190.46  4031.4  190.96  4081.4   190.7
  4131.4  191.29  4341.4  191.73  4351.4  191.37  4381.4  191.89  4918.8   190.8
  4941.5  190.88 4946.48  191.35 4984.72  180.93 4989.89  180.53 4995.38  180.99
 5039.73  191.65 5052.28  191.29  5138.8  190.97  5178.8  191.92  5508.4   193.9
#Mann= 5 ,-1 , 0
  1317.2     .99       0  3581.4     .06       0  4918.8     .07       0
 4946.48     .04       0 5052.28     .06       0
#XS Ineff= 2 , 0
       0    4817   190.6    5180       0   190.6
Permanent Ineff=
       F       F
Bank Sta=4946.48,5039.73
Pilot Channel=178.352,2,0.04
Exp/Cntr=0.3,0.1

Type RM Length L Ch R = 1 ,13928.6 ,1073.4,1004.95,984.8
BEGIN DESCRIPTION:
Channel Improvements, B/W 6', Side Slopes 4:1 X21
END DESCRIPTION:
XS GIS Cut Line= 5
 2989944.049399813923425.4778887      2987036.43     13922241.16
      2986493.53     13922036.53      2985766.73     13922009.82
      2984996.85     13922296.37
#Sta/Elev= 30
  1584.2  191.88  2414.2  189.87  2874.2  190.16  2894.2   189.8  3484.2   190.1
  3574.2   190.6  3794.2  190.26  4364.2  191.26  4374.2   191.1  4384.2  189.77
  4394.2  190.25  4404.2  191.63  4454.2  190.23  4723.8  188.79  4850.4   189.1
 4959.51  187.47 4996.48  180.28 5002.55   180.1 5009.39  180.36 5045.01  188.75
 5054.28  188.85  5253.8  189.51  5303.9  188.33  5413.9  189.23  5453.9  188.78
  5653.9  189.06  6111.2  191.17  6171.2  190.96  6181.2  190.35  6852.7  192.35
#Mann= 5 ,-1 , 0
  1584.2     .99       0  4404.2     .06       0 4959.51     .04       0
 5054.28     .06       0  5413.9     .99       0
Bank Sta=4959.51,5045.01
Pilot Channel=177.725,2,0.04
Exp/Cntr=0.3,0.1

Type RM Length L Ch R = 1 ,12923.6 ,650.4,677.29,884
BEGIN DESCRIPTION:
Channel Improvements, B/W 6', Side Slopes 4:1 XS22
END DESCRIPTION:
XS GIS Cut Line= 4
  2987538.40759313921287.1434025       2987094.4     13921155.06
      2986530.26      13921142.3 2986300.3540056 13921137.772512
#Sta/Elev= 29
  4246.4   192.6  4256.4   191.6  4279.8  190.74  4286.4   190.5  4316.4   190.6
  4336.4   189.9  4366.4   189.8  4396.4   190.8  4556.4   190.6  4636.4   189.1
  4709.6   188.3  4729.6   187.8  4747.4  188.26  4782.9  188.09    4829  187.58
 4867.64  185.45 4898.68  179.62 4903.58  179.36  4911.2   179.7 4940.03   185.1
 4961.43     187  4968.8  187.01  5031.4  186.79 5037.33  186.85  5078.5  187.27
  5129.9  188.22  5197.1  189.04  5249.6   189.1  5503.9   190.4
#Mann= 3 , 0 , 0
  4246.4     .06       0 4867.64     .04       0 4940.03     .06       0
Bank Sta=4867.64,4940.03
Pilot Channel=177.195,2,0.04
Exp/Cntr=0.3,0.1

Type RM Length L Ch R = 1 ,12246.3 ,835.6,773.33,856.3
BEGIN DESCRIPTION:
Channel Improvements, B/W 6', Side Slopes 4:1 XS23
END DESCRIPTION:
XS GIS Cut Line= 4
  2988023.33524113920416.0128142      2987145.82     13920524.75
      2986778.91     13920449.27  2986000.895148 13920546.506857
#Sta/Elev= 30
    4005   194.7    4235   193.6    4415   191.5    4465   191.9    4545   190.6
    4555   190.7    4565   192.1    4585   192.4    4615   190.9    4685   190.6
    4715   189.5    4735   189.8  4953.1  185.23 4959.79   184.4  4975.9     184
 5104.58  182.75 5120.22   179.1 5125.38   178.8 5131.42  179.25 5161.23  184.55
  5169.2   185.8  5189.2   185.6  5263.8   186.9  5293.8   187.7  5313.8     189
  5483.8   190.8  5633.8   193.8  5733.8   194.4  5763.8   195.6  6047.9   196.1
#Mann= 3 ,-1 , 0
    4005     .06       0 5104.58     .04       0 5161.23     .06       0
Bank Sta=4975.9,5161.23
Pilot Channel=176.689,2,0.04
Exp/Cntr=0.3,0.1