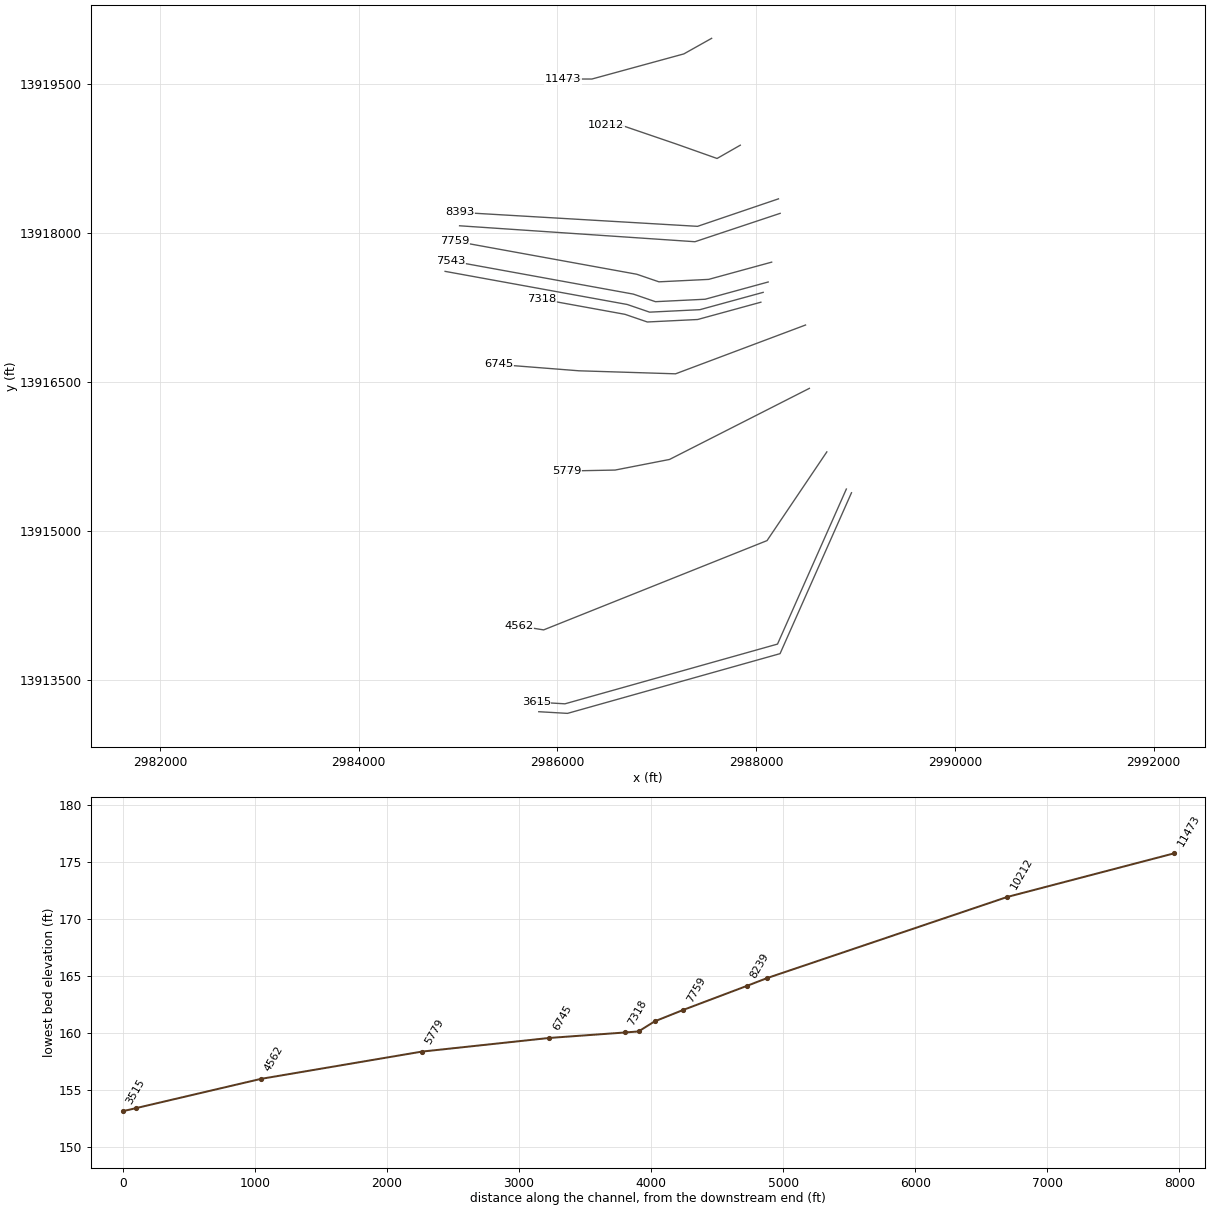
HEC-RAS study K155-00-00.prj: K155-00-00

--- K155-00-00.g01 (geometry) --- (continued)

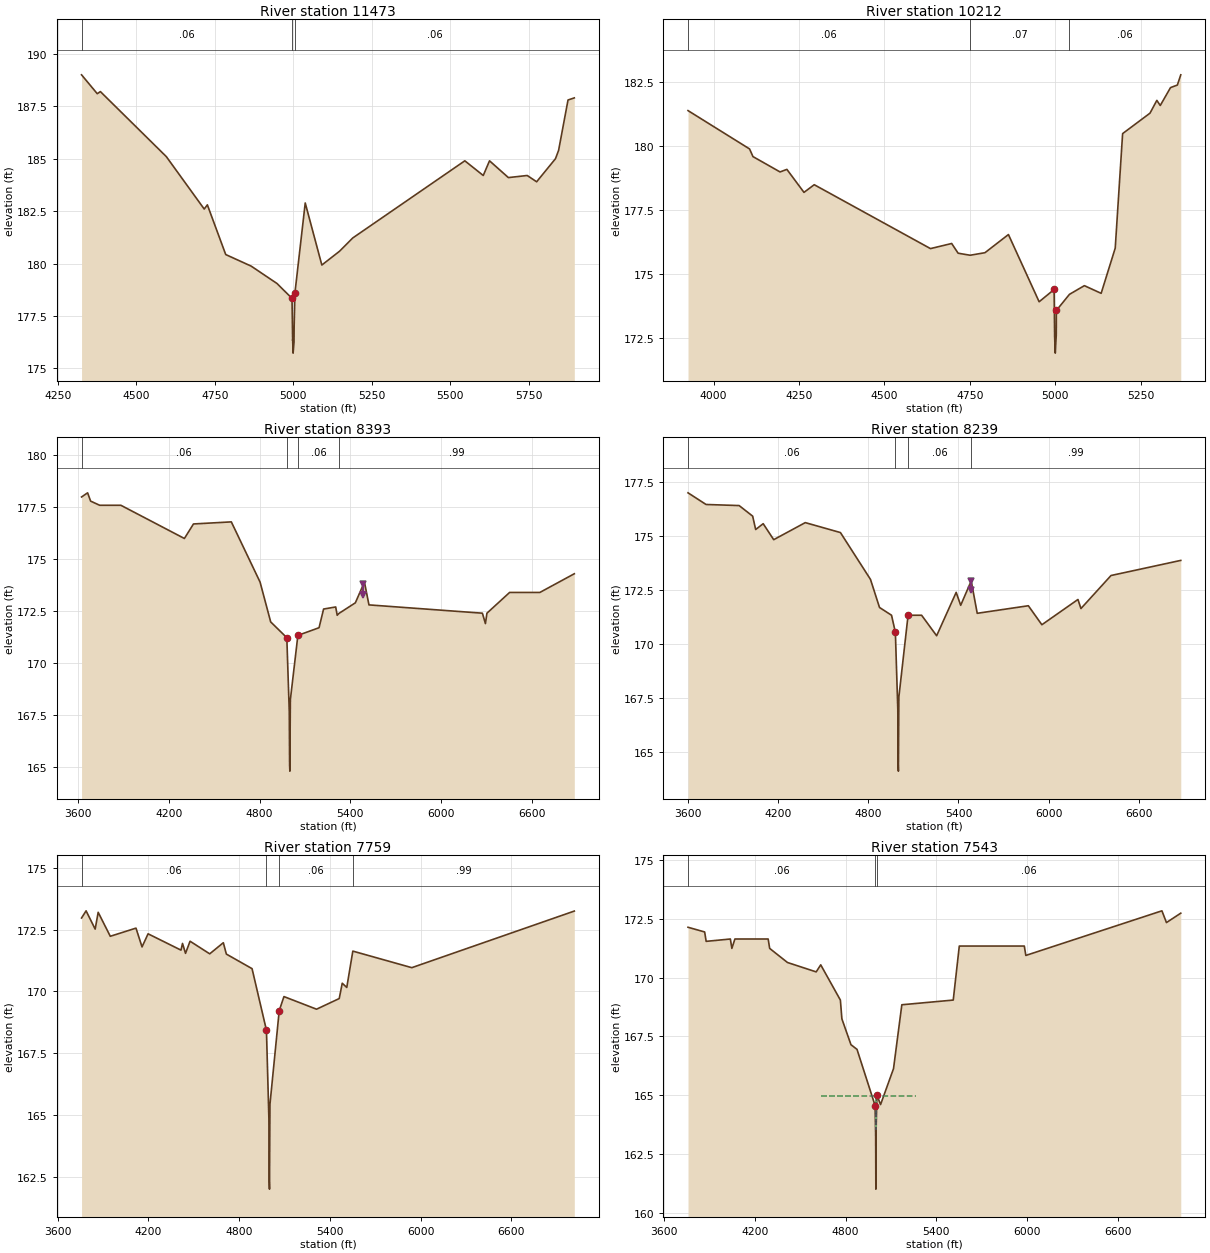
Type RM Length L Ch R = 1 ,11473   ,1074.3,1261,836.2
BEGIN DESCRIPTION:
Cross Section K155-00-00-X08
END DESCRIPTION:
XS GIS Cut Line= 4
 2987552.832984513919961.8570555       2987273.1     13919805.01
      2986348.35     13919552.11 2986058.3998047     13919552.11
#Sta/Elev= 30
  4325.3     189  4375.3   188.1  4385.3   188.2  4595.3   185.1    4716   182.6
    4726   182.8  4784.5  180.43  4865.4  179.88  4947.8  179.05  4995.6  178.34
  4997.6  176.34 4997.71  176.37  4999.1  175.73    5002  176.25  5002.4  176.99
  5004.9   178.6  5037.7  182.89  5090.6  179.93  5147.1  180.59    5189  181.22
    5546   184.9  5604.7   184.2  5624.7   184.9  5684.7   184.1  5744.7   184.2
  5774.7   183.9  5834.7     185  5844.7   185.4  5874.7   187.8  5894.7   187.9
#Mann= 3 ,-1 , 0
  4325.3     .06       0  4995.6     .07       0  5004.9     .06       0
Bank Sta=4995.6,5004.9
Exp/Cntr=0.3,0.1

Type RM Length L Ch R = 1 ,10212   ,1055.9,1819,1212.9
BEGIN DESCRIPTION:
Cross Section K155-00-00-X07
END DESCRIPTION:
XS GIS Cut Line= 5
 2987841.225804413918885.6414305      2987607.58     13918751.93
      2987190.96     13918899.63      2986632.59     13919090.48
 2986492.6191148 13919087.871084
#Sta/Elev= 30
  3925.4   181.4  4105.4   179.9  4115.4   179.6  4194.6     179  4214.6   179.1
  4264.6   178.2  4294.6   178.5  4634.6     176  4696.6   176.2  4715.4  175.82
  4750.7  175.74    4794  175.84  4862.6  176.55  4952.4  173.92  4996.2   174.4
  4997.8  172.54  4999.6  171.91  5002.5  172.62  5002.8  173.58  5041.1  174.21
  5084.7  174.55  5133.8  174.25    5175  176.02  5196.6   180.5  5276.7   181.3
  5296.7   181.8  5306.7   181.6  5336.7   182.3  5356.7   182.4  5366.7   182.8
#Mann= 3 ,-1 , 0
  3925.4     .06       0  4750.7     .07       0  5041.1     .06       0
Bank Sta=4996.2,5002.8
Exp/Cntr=0.3,0.1

Type RM Length L Ch R = 1 ,8393    ,154,154,154
BEGIN DESCRIPTION:
Cross Section K155-00-00-X6
END DESCRIPTION:
XS GIS Cut Line= 3
      2988225.74     13918345.46      2987411.22     13918068.52
      2985017.62     13918209.23
#Sta/Elev= 30
    3623     178    3663   178.2    3683   177.8    3743   177.6    3883   177.6
    4303     176    4363   176.7  4613.3   176.8  4803.3   173.9  4873.5  171.98
  4980.2  171.22  4996.4  167.65  4998.6  165.11  5000.3  164.79  5003.6  168.23
  5053.3  171.33  5193.3   171.7  5223.3   172.6  5303.3   172.7  5313.3   172.3
    5325  172.39  5433.3   172.9  5493.3   173.9  5523.3   172.8  6273.3   172.4
  6293.3   171.9  6303.3   172.4  6453.3   173.4  6653.3   173.4    6881   174.3
#Mann= 4 ,-1 , 0
    3623     .06       0  4980.2     .07       0  5053.3     .06       0
    5325     .99       0
Levee=0,,,-1,5486.94,173.28,,
Bank Sta=4980.2,5053.3
Exp/Cntr=0.3,0.1

Type RM Length L Ch R = 1 ,8239    ,400,480,360
BEGIN DESCRIPTION:
Cross Section K155-00-00-X6A
END DESCRIPTION:
XS GIS Cut Line= 3
       2988242.4      13918199.3      2987385.02      13917913.6
      2985016.46      13918074.1
#Sta/Elev= 30
  3600.9  176.99  3720.9  176.45  3940.9   176.4  4030.9  175.91  4050.9  175.29
  4100.9  175.56  4170.9  174.82  4380.9  175.61  4614.7  175.15  4814.7  172.98
  4874.7  171.68  4954.7  171.32  4980.2  170.53  4996.4  166.96  4998.6  164.42
  5000.3   164.1  5003.6  167.54  5064.7  171.32  5154.7  171.32  5254.7  170.37
  5384.7  172.38  5414.7  171.78  5484.7  172.91  5524.7  171.41  5864.7  171.76
  5954.7  170.88  6194.7  172.05  6214.7  171.63  6414.7  173.16  6878.7  173.86
#Mann= 4 ,-1 , 0
  3600.9     .06       0  4980.2     .07       0  5064.7     .06       0
  5484.7     .99       0
Levee=0,,,-1,5484.54,172.47,,
Bank Sta=4980.2,5064.7
Exp/Cntr=0.3,0.1

Type RM Length L Ch R = 1 ,7759    ,218,216,182.7
BEGIN DESCRIPTION:
Cross Section K155-00-00-X6B - DIRT RD - XS4
END DESCRIPTION:
XS GIS Cut Line= 5
      2988157.05       13917708.      2987522.79      13917534.3
      2987022.51      13917509.7      2986799.71       13917586.
      2984965.21      13917919.9
#Sta/Elev= 30
  3757.5  172.97  3787.5  173.26  3847.5  172.52  3867.5   173.2  3947.5  172.23
  4117.5  172.56  4157.5   171.8  4197.5  172.33  4415.1  171.67  4425.1  171.94
  4445.1  171.54  4475.1  172.03  4605.1  171.52  4695.1  171.97  4715.1  171.51
  4885.1  170.92  4980.2  168.43  4996.4  164.86  4998.6  162.32  5000.3     162
  5003.6  165.44  5064.7  169.22    5096  169.79  5311.5  169.28  5461.5  169.71
  5481.5  170.33  5511.5  170.16  5551.5  171.63  5941.5  170.96  7016.2  173.25
#Mann= 4 ,-1 , 0
  3757.5     .06       0  4980.2     .07       0  5064.7     .06       0
  5551.5     .99       0
#XS Ineff= 2 , 0
       0    4536  164.95    5102       0  164.95
Permanent Ineff=
       F       F
Bank Sta=4980.2,5064.7
Exp/Cntr=0.5,0.3

Type RM Length L Ch R = 1 ,7543    ,123,123,123
BEGIN DESCRIPTION:
K155-00-00-S1_DIRT RD -US - XS3
END DESCRIPTION:
XS GIS Cut Line= 5
      2988122.06     13917508.08       2987487.8     13917334.39
      2986987.51     13917309.71      2986764.71      13917386.1
      2984930.21     13917719.93
#Sta/Elev= 30
  3758.1  172.15  3868.1  171.95  3878.1  171.55  4038.1  171.65  4048.1  171.25
  4068.1  171.65  4288.1  171.65  4298.1  171.25  4415.7  170.65  4605.7  170.25
  4635.7  170.55  4765.7  169.05  4775.7  168.25  4835.7  167.15  4875.7  166.95
  4995.2  164.56  4999.1  163.23  5000.3     161  5000.9  163.21  5007.3     165
  5031.5   164.6  5117.1  166.13  5172.1  168.85  5512.1  169.05  5552.1  171.35
  5982.1  171.35  5992.1  170.95  6892.1  172.85  6922.1  172.35  7016.8  172.75
#Mann= 3 ,-1 , 0
  3758.1     .06       0  4995.2     .07       0  5007.3     .06       0
#XS Ineff= 3 ,-1
                          4635.7 4997.98  164.95 5001.99  5265.8  164.95
Permanent Ineff=
       F       F       F
Bank Sta=4995.2,5007.3
Exp/Cntr=0.5,0.3

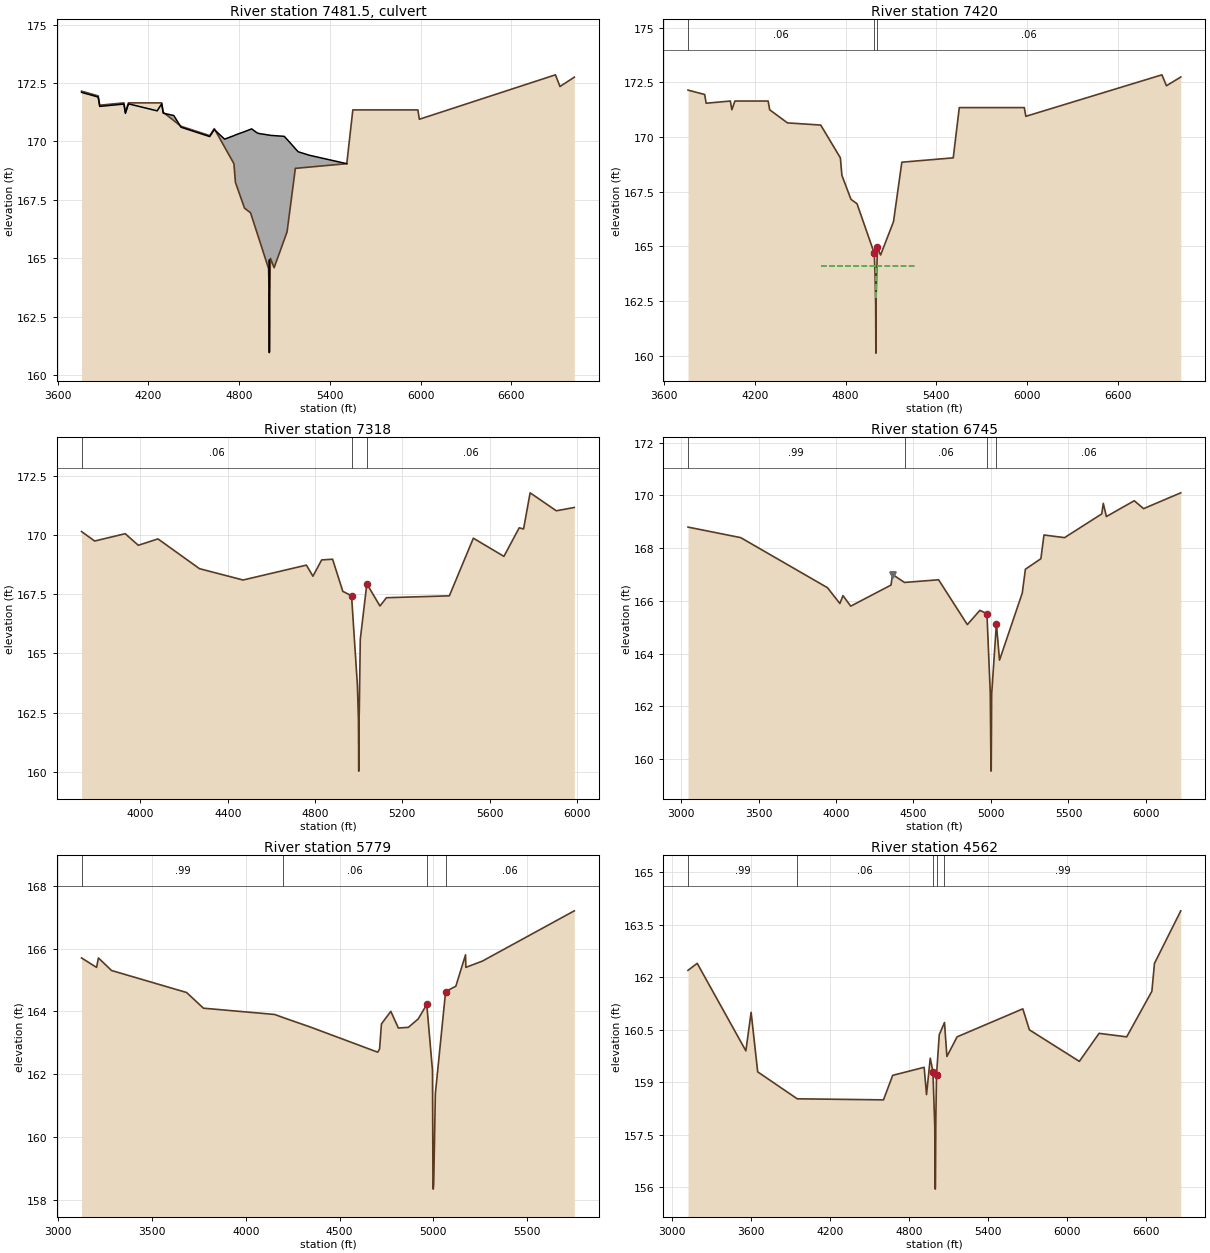
Type RM Length L Ch R = 2 ,7481.5  ,,,
BEGIN DESCRIPTION:
DIRT RD (NOT HOUSE RD);
Removed low survey TOR shots because they were taken adjacent to (u/s or d/s of) high TOR shots.  -khh
Structure ID: K155-00-00-S1
END DESCRIPTION:
Bridge Culvert--1,0,-1,-1, 0
Deck Dist Width WeirC Skew NumUp NumDn MinLoCord MaxHiCord MaxSubmerge Is_Ogee
10,103,2.6,0, 44, 44, , , 0.95, 0, ,,,
  3758.1  3868.1  3878.1  4038.1  4048.1  4068.1    4074  4258.1  4288.1  4298.1
    4354  4368.1    4414  4415.7    4534  4605.7  4635.7    4704  4765.7  4775.7
  4835.7  4875.7    4883  4905.7  4916.6  4921.6  4939.7  4963.6    4990  4995.2
  4997.9  4999.1  5000.3  5000.9  5002.1  5007.3  5010.5  5098.3  5117.1  5152.1
  5172.1  5190.9  5265.5  5512.3
   172.1   171.9   171.5   171.6   171.2   171.6   171.6  171.31  171.61  171.21
  171.13  171.11  170.63  170.61  170.36  170.21  170.51   170.1  170.25  170.28
  170.42  170.52  170.54  170.43  170.38  170.36  170.33  170.31  170.28  170.28
  170.27  170.27  170.27  170.27  170.27  170.26  170.26  170.22  170.09  169.84
  169.69  169.56  169.41  169.05
                                                                                
                                                                                
                                                                                
                                                                                
                                
  3758.1  3868.1  3878.1  4038.1  4048.1  4068.1    4074  4258.1  4288.1  4298.1
    4354  4368.1    4414  4415.7    4534  4605.7  4635.7    4704  4765.7  4775.7
  4835.7  4875.7    4883  4905.7  4916.6  4921.6  4939.7  4963.6    4990  4995.2
  4997.9  4999.1  5000.3  5000.9  5002.1  5007.3  5010.5  5098.3  5117.1  5152.1
  5172.1  5190.9  5265.5  5512.3
   172.1   171.9   171.5   171.6   171.2   171.6   171.6  171.31  171.61  171.21
  171.13  171.11  170.63  170.61  170.36  170.21  170.51   170.1  170.25  170.28
  170.42  170.52  170.54  170.43  170.38  170.36  170.33  170.31  170.28  170.28
  170.27  170.27  170.27  170.27  170.27  170.26  170.26  170.22  170.09  169.84
  169.69  169.56  169.41  169.05
                                                                                
                                                                                
                                                                                
                                                                                
                                
BR Coef= 1 , 1 , 0 ,1.25, 0 ,,,0.8,-1,2,0,
WSPro=,,,, 1 ,,,, 0 ,,,, 0 ,,,,-1 ,-1 ,-1 , 0 , 0 , 0 , 0 , 0
Culvert=1,4,,103,0.013,0.4,1,1,3,160.95,5000,160.12,5000,Culvert #1  , 0 ,10
Culvert Bottom n=0.013
BC Design=,, 0 ,, 0 ,,,,,,
BC HTab HWMax=172.85

Type RM Length L Ch R = 1 ,7420    ,102,102,102
BEGIN DESCRIPTION:
K155-00-00-S1_DIRT RD -DS - XS2
END DESCRIPTION:
XS GIS Cut Line= 5
      2988071.43     13917403.57      2987435.07     13917229.31
      2986928.76     13917204.33      2986703.75     13917281.48
      2984870.73     13917615.04
#Sta/Elev= 30
  3758.1  172.15  3868.1  171.95  3878.1  171.55  4038.1  171.65  4048.1  171.25
  4068.1  171.65  4288.1  171.65  4298.1  171.25  4415.7  170.65  4635.7  170.55
  4765.7  169.05  4775.7  168.25  4835.7  167.15  4875.7  166.95    4990  164.68
  4995.2  163.67  4999.1  162.34  5000.3  160.11  5000.9  162.32  5010.5  164.95
  5031.5   164.6  5117.1  166.13  5172.1  168.85  5512.1  169.05  5552.1  171.35
  5982.1  171.35  5992.1  170.95  6892.1  172.85  6922.1  172.35  7016.8  172.75
#Mann= 3 ,-1 , 0
  3758.1     .06       0    4990     .07       0  5010.5     .06       0
#XS Ineff= 3 ,-1
    3800  4635.7     170  4635.7 4997.98  164.12 5001.99  5265.8  164.12
Permanent Ineff=
       F       F       F
Bank Sta=4990,5010.5
Exp/Cntr=0.5,0.3

Type RM Length L Ch R = 1 ,7318    ,573.04,573.04,573.04
BEGIN DESCRIPTION:
K155-00-00-S1_DIRT RD -DS - XS1
END DESCRIPTION:
XS GIS Cut Line= 5
      2988048.48     13917304.51     2987412.113     13917130.25
     2986905.806     13917105.27     2986680.795     13917182.42
      2985842.19     13917335.02
#Sta/Elev= 30
  3730.6  170.16  3790.6  169.76  3930.6  170.07  3990.6  169.58  4080.6  169.85
  4270.6  168.59  4470.4  168.11  4760.4  168.74  4790.4  168.27  4830.4  168.96
  4880.4  168.99  4927.3  167.63  4967.3  167.44    4994  163.67 4998.79  162.21
 5000.27  160.02 5001.09  161.99 5002.73  162.58  5007.3   165.6  5037.3  167.95
  5097.3  167.01  5127.3  167.36  5415.2  167.44  5525.2  169.88  5665.2  169.11
  5735.2  170.32  5755.2  170.27  5785.2   171.8  5905.2  171.04  5987.6  171.18
#Mann= 3 ,-1 , 0
  3730.6     .06       0  4967.3     .07       0  5037.3     .06       0
#XS Ineff= 2 , 0
       0    4535  164.12    5101       0  164.12
Permanent Ineff=
       F       F
Bank Sta=4967.3,5037.3
Exp/Cntr=0.3,0.1

Type RM Length L Ch R = 1 ,6745    ,966,966,966
BEGIN DESCRIPTION:
Cross Section K155-00-00-X5
END DESCRIPTION:
XS GIS Cut Line= 4
      2988497.85     13917074.79      2987189.98     13916583.28
      2986217.59     13916613.74 2985410.133313513916677.1517488
#Sta/Elev= 30
  3044.9   168.8  3384.9   168.4  3944.9   166.5  4024.9   165.9  4044.9   166.2
  4094.9   165.8  4354.9   166.6  4364.9     167  4442.1   166.7  4662.1   166.8
  4847.4   165.1  4928.6  165.64  4974.1  165.51  4995.5  162.51  5000.1  159.54
  5001.6  159.56  5004.4  162.45    5035  165.13  5055.1  163.75  5202.1   166.3
  5222.1   167.2  5322.1   167.6  5342.1   168.5  5474.9   168.4  5714.9   169.3
  5724.9   169.7  5744.9   169.2  5924.9   169.8  5984.9   169.5  6224.9   170.1
#Mann= 4 ,-1 , 0
  3044.9     .99       0  4442.1     .06       0  4974.1     .07       0
    5035     .06       0
Levee=-1,4364.99,167,0,,,,
Bank Sta=4974.1,5035
Exp/Cntr=0.3,0.1

Type RM Length L Ch R = 1 ,5779    ,1217,1217,1217
BEGIN DESCRIPTION:
Cross Section K155-00-00-X04
END DESCRIPTION:
XS GIS Cut Line= 4
      2988536.52     13916436.83       2987129.2     13915720.86
      2986581.16     13915613.94 2986091.258657713915604.5408718
#Sta/Elev= 28
  3124.4   165.7  3204.4   165.4  3214.4   165.7  3284.4   165.3  3684.4   164.6
  3774.4   164.1  4154.4   163.9    4200   163.8  4344.4   163.5  4703.4   162.7
  4713.4   162.8  4723.4   163.6  4773.4     164  4813.5  163.47  4866.8  163.49
  4919.7  163.76  4965.1  164.22  4995.5  162.12  4998.1  158.54  4999.5  158.34
    5002  158.49  5010.8  161.38  5065.5  164.63    5120   164.8  5171.8   165.8
  5173.4   165.4  5261.7   165.6  5751.7   167.2
#Mann= 4 ,-1 , 0
  3124.4     .99       0    4200     .06       0  4965.1     .07       0
  5065.5     .06       0
Bank Sta=4965.1,5065.5
Exp/Cntr=0.3,0.1

Type RM Length L Ch R = 1 ,4562    ,982.73,947,947
BEGIN DESCRIPTION:
Cross Section K155-00-00-X3
END DESCRIPTION:
XS GIS Cut Line= 4
      2988712.06     13915796.91       2988110.5     13914903.68
      2985862.24     13914004.37 2985615.437629513914044.1385093
#Sta/Elev= 30
  3119.2   162.2  3189.2   162.4  3559.2   159.9  3599.2     161  3649.2   159.3
    3950  158.53  4606.1   158.5  4676.1   159.2  4915.4  159.43  4933.5  158.65
  4961.8  159.69  4982.2  159.31  4996.3  157.73  4998.8  155.98  5000.1  155.95
  5001.5  156.05  5004.2  157.91  5009.5  159.21  5030.3  160.36  5070.2  160.71
  5088.5  159.74  5166.1   160.3  5666.1   161.1  5716.1   160.5  6096.1   159.6
  6246.1   160.4  6456.1   160.3  6647.6   161.6  6667.6   162.4  6867.6   163.9
#Mann= 5 ,-1 , 0
  3119.2     .99       0    3950     .06       0  4982.2     .07       0
  5009.5     .06       0  5070.2     .99       0
#XS Ineff= 2 , 0
       0                  5166.1       0   160.3
Permanent Ineff=
       F       F
Bank Sta=4982.2,5009.5
Exp/Cntr=0.3,0.1

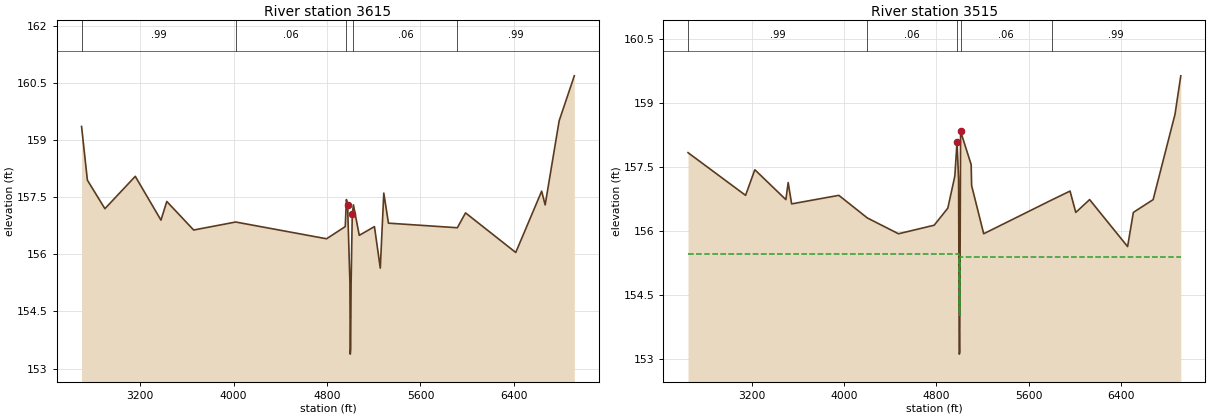
Type RM Length L Ch R = 1 ,3615    ,103.77,100,100
BEGIN DESCRIPTION:
K155-00-00-S1A_PRIVATE RD -US - XS4
END DESCRIPTION:
XS GIS Cut Line= 4
      2988908.56      13915422.9      2988215.89     13913861.52
        2986077.     13913259.96      2985787.81     13913276.74
#Sta/Elev= 30
  2697.9  159.36  2747.9  157.95  2897.9   157.2  3157.9  158.05  3377.9   156.9
  3427.9  157.39  3657.9  156.64  4017.9  156.85  4796.1  156.41  4956.1  156.73
  4966.1  157.44  4976.1   157.3  4996.1  155.25 4998.83  153.38 5002.18  153.52
  5006.1  155.22  5016.1  157.05  5026.1   157.3  5076.1   156.5  5206.1  156.73
  5256.1  155.64  5286.1  157.61  5326.1  156.82  5916.1   156.7  5986.1  157.09
  6416.1  156.05    6638  157.66    6668   157.3    6788  159.51  6917.6  160.69
#Mann= 5 ,-1 , 0
  2697.9     .99       0  4017.9     .06       0  4966.1     .07       0
  5026.1     .06       0  5916.1     .99       0
#XS Ineff= 2 , 0
       0 4896.75  155.46    5103       0  155.56
Permanent Ineff=
       F       F
Bank Sta=4976.1,5016.1
Exp/Cntr=0.5,0.3

Type RM Length L Ch R = 1 ,3515    ,29,29,29
BEGIN DESCRIPTION:
K155-00-00-S1A_PRIVATE RD -US - XS3
END DESCRIPTION:
XS GIS Cut Line= 5
 2988960.263684613915385.4706467      2988958.52     13915381.54
       2988241.5     13913765.22      2986102.61     13913163.66
 2985813.422274513913180.4390539
#Sta/Elev= 30
  2642.2  157.83  3142.2  156.83  3222.5  157.43  3492.2  156.73  3512.2  157.13
  3542.2  156.63  3952.2  156.83    4200   156.3  4470.4  155.93  4780.4  156.13
  4898.9  156.53  4959.7  157.28  4978.8  158.08  4992.4  157.21  4997.3  153.71
  4998.7  153.11  5002.1  153.15  5009.8  158.33  5101.7  157.55  5105.5  157.06
  5210.4  155.93    5800  156.72  5960.4  156.93  6010.4  156.43  6130.4  156.73
  6460.4  155.63  6510.4  156.43  6682.3  156.73  6872.3  158.73  6922.3  159.63
#Mann= 5 ,-1 , 0
  2642.2     .99       0    4200     .06       0  4978.8     .07       0
  5009.8     .06       0    5800     .99       0
#XS Ineff= 2 , 0
       0 4996.75  155.46 5003.36       0  155.39
Permanent Ineff=
       F       F
Bank Sta=4978.8,5009.8
Exp/Cntr=0.5,0.3