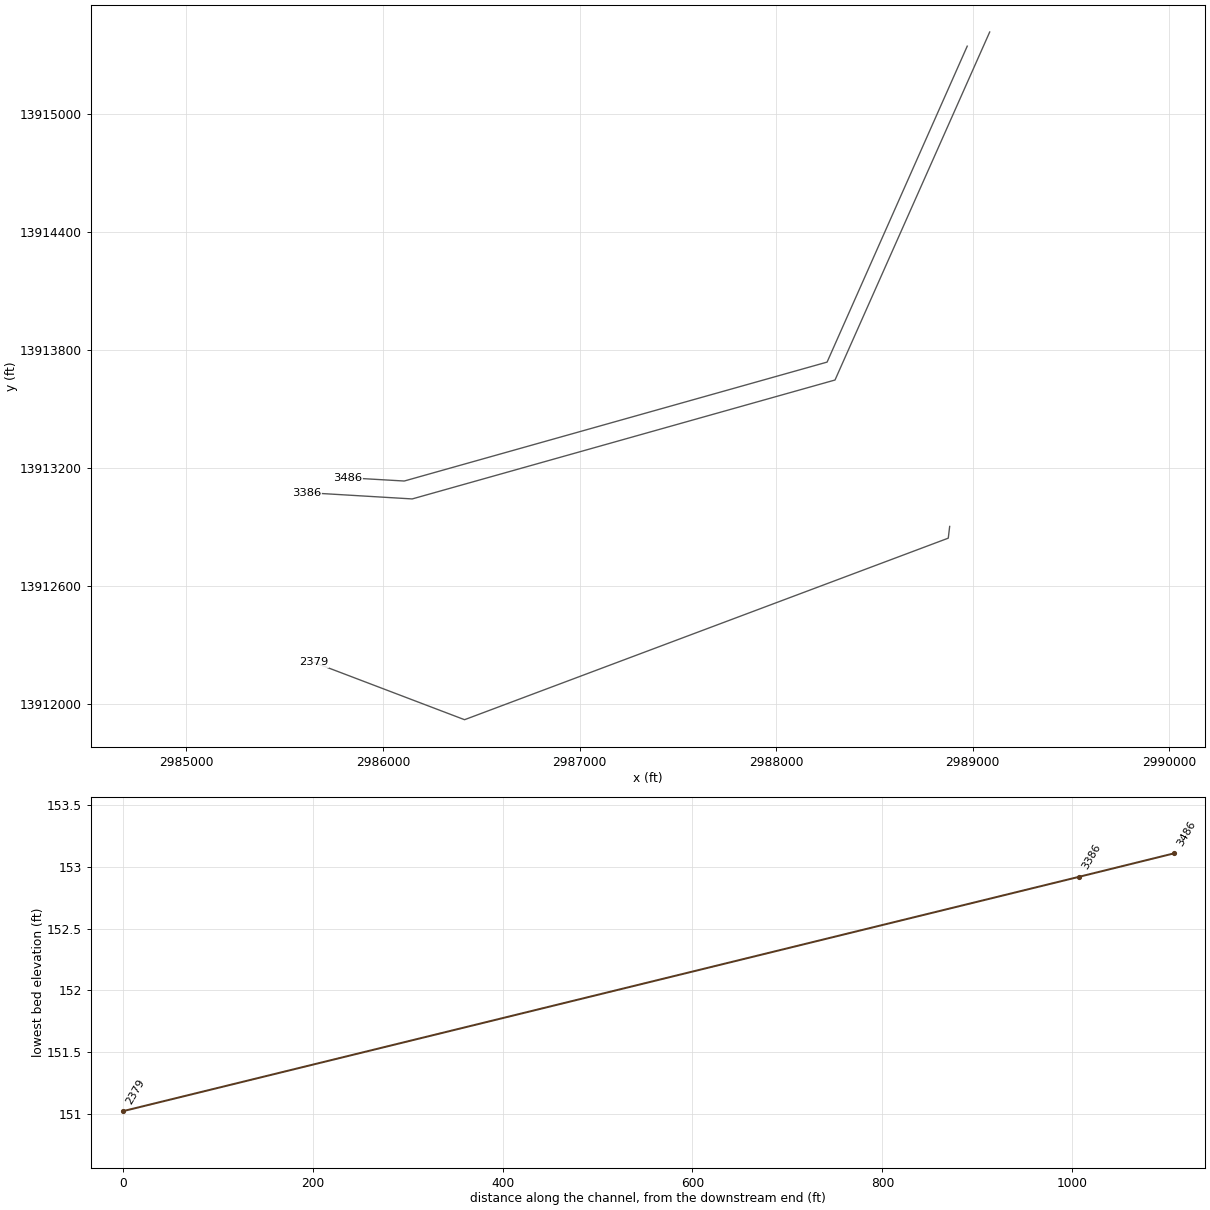
HEC-RAS study K155-00-00.prj: K155-00-00

--- K155-00-00.g01 (geometry) --- (continued)

Type RM Length L Ch R = 2 ,3500.5  ,,,
BEGIN DESCRIPTION:
3500' US CONFLUENCE WITH CYPRESS CREEK
Structure ID: K155-00-00-S1A
END DESCRIPTION:
Bridge Culvert--1,0,-1,-1, 0
Deck Dist Width WeirC Skew NumUp NumDn MinLoCord MaxHiCord MaxSubmerge Is_Ogee
10,15,3,0, 50, 50, , , 0.95, 0, ,,,
  2642.2  3142.2  3222.5  3312.2  3332.2  3362.2  3462.2  3492.2  3512.2  3542.2
  3562.2  3942.2  3952.2  3962.2  4272.2  4282.2  4292.2  4470.4  4590.4  4780.4
  4890.4  4898.9    4930  4955.9  4959.7  4978.8  4992.4  4997.3  4998.7  5002.1
  5002.8  5009.8  5058.1  5101.7  5105.5  5160.4  5210.4  5960.4  6010.4  6130.4
  6390.4  6450.4  6460.4  6510.4  6520.4  6590.4  6682.3  6692.3  6872.3  6922.3
   157.8   156.8   157.4   157.3   156.9   157.2     157   156.7   157.1   156.6
   156.9   156.6   156.8   156.5   156.2     156   156.4   155.9   156.2  156.19
  156.71  156.51  156.95   157.7  157.72  158.06  157.85  157.87  157.88  157.93
  157.95  158.31  157.85  157.53  157.04  156.61   155.9   156.9   156.4   156.7
   155.8   155.9   155.6   156.4   156.2   156.7   156.7     157   158.7   159.6
   157.8   156.8   157.4   157.3   156.9   157.2     157   156.7   157.1   156.6
   156.9   156.6   156.8   156.5   156.2     156   156.4   155.9   156.2   156.1
   156.7   156.5  156.94  157.21  157.25  158.05  157.18  153.68  153.08  153.12
   153.5   158.3  157.84  157.52  157.03   156.6   155.9   156.9   156.4   156.7
   155.8   155.9   155.6   156.4   156.2   156.7   156.7     157   158.7   159.6
  2642.2  3142.2  3222.5  3312.2  3332.2  3362.2  3462.2  3492.2  3512.2  3542.2
  3562.2  3942.2  3952.2  3962.2  4272.2  4282.2  4292.2  4470.4  4590.4  4780.4
  4890.4  4898.9    4930  4955.9  4959.7  4978.8  4992.4  4997.3  4998.7  5002.1
  5002.8  5009.8  5058.1  5101.7  5105.5  5160.4  5210.4  5960.4  6010.4  6130.4
  6390.4  6450.4  6460.4  6510.4  6520.4  6590.4  6682.3  6692.3  6872.3  6922.3
   157.8   156.8   157.4   157.3   156.9   157.2     157   156.7   157.1   156.6
   156.9   156.6   156.8   156.5   156.2     156   156.4   155.9   156.2  156.19
  156.71  156.51  156.95   157.7  157.72  158.06  157.85  157.87  157.88  157.93
  157.95  158.31  157.85  157.53  157.04  156.61   155.9   156.9   156.4   156.7
   155.8   155.9   155.6   156.4   156.2   156.7   156.7     157   158.7   159.6
   157.8   156.8   157.4   157.3   156.9   157.2     157   156.7   157.1   156.6
   156.9   156.6   156.8   156.5   156.2     156   156.4   155.9   156.2   156.1
   156.7   156.5  156.94  157.21  157.25  158.05  157.18  153.68  153.08  153.12
   153.5   158.3  157.84  157.52  157.03   156.6   155.9   156.9   156.4   156.7
   155.8   155.9   155.6   156.4   156.2   156.7   156.7     157   158.7   159.6
BR Coef= 1 , 1 , 0 ,1.25, 0 ,,,0.8,-1,2,0,
WSPro=,,,, 1 ,,,, 0 ,,,, 0 ,,,,-1 ,-1 ,-1 , 0 , 0 , 0 , 0 , 0
Culvert=1,2.5,,15,0.015,0.4,1,1,3,152.96,4998,153.15,4998,Culvert #1  , 0 ,10
Culvert Bottom n=0.015
Culvert=1,2.5,,15,0.015,0.4,1,1,3,152.89,5002.1,153.06,5002.1,Culvert #2  , 0 ,10
Culvert Bottom n=0.015
BC Design=,, 0 ,, 0 ,,,,,,
BC HTab HWMax=159.63

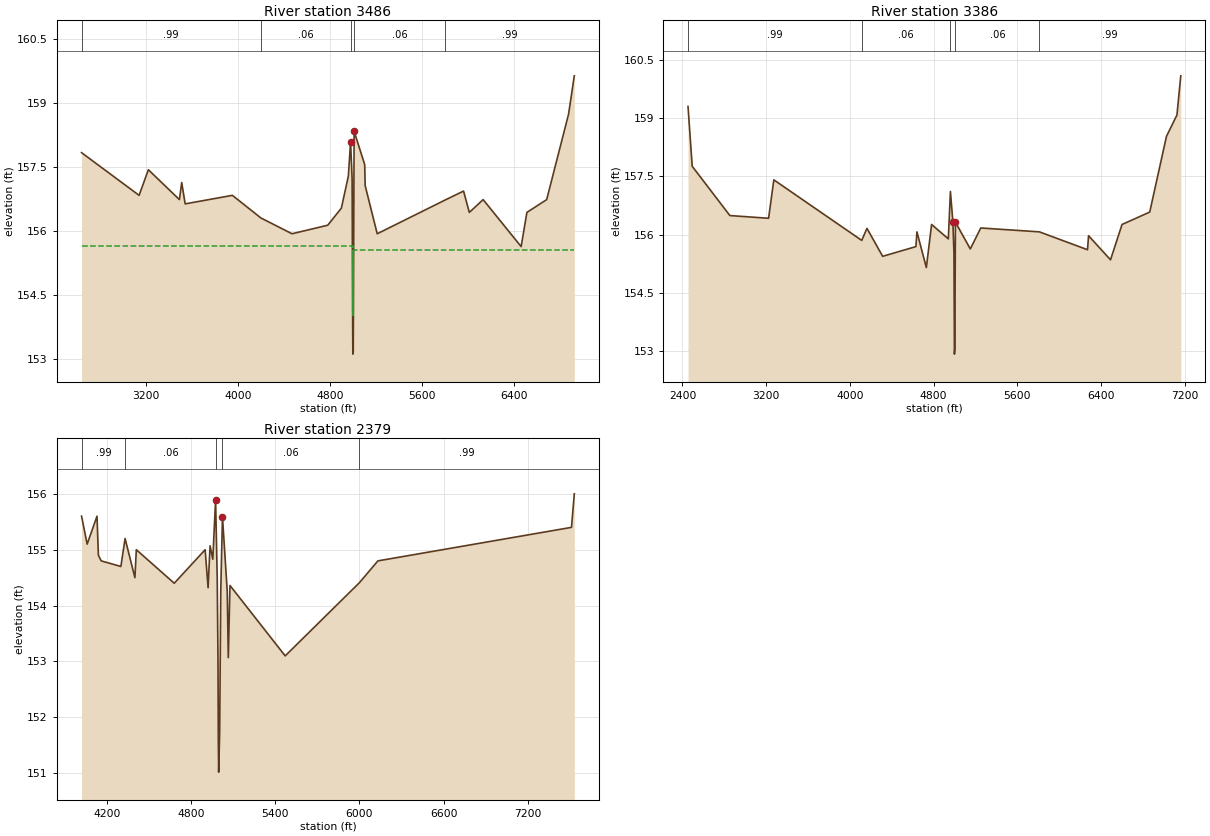
Type RM Length L Ch R = 1 ,3486    ,100,100,100
BEGIN DESCRIPTION:
K155-00-00-S1A_PRIVATE RD -DS - XS2
END DESCRIPTION:
XS GIS Cut Line= 4
 2988972.634359313915346.8294466      2988259.59     13913739.47
      2986108.42     13913134.45 2985821.872412613913151.0751674
#Sta/Elev= 30
  2642.2  157.83  3142.2  156.83  3222.5  157.43  3492.2  156.73  3512.2  157.13
  3542.2  156.63  3952.2  156.83    4200   156.3  4470.4  155.93  4780.4  156.13
  4898.9  156.53  4959.7  157.28  4978.8  158.08  4992.4  157.21  4997.3  153.71
  4998.7  153.11  5002.1  153.15  5009.8  158.33  5101.7  157.55  5105.5  157.06
  5210.4  155.93    5800  156.72  5960.4  156.93  6010.4  156.43  6130.4  156.73
  6460.4  155.63  6510.4  156.43  6682.3  156.73  6872.3  158.73  6922.3  159.63
#Mann= 5 ,-1 , 0
  2642.2     .99       0    4200     .06       0  4978.8     .07       0
  5009.8     .06       0    5800     .99       0
#XS Ineff= 2 , 0
       0 4996.75  155.65 5003.36       0  155.56
Permanent Ineff=
       F       F
Bank Sta=4978.8,5009.8
Exp/Cntr=0.5,0.3

Type RM Length L Ch R = 1 ,3386    ,1006,1007,1008
BEGIN DESCRIPTION:
K155-00-00-S1A_PRIVATE RD -DS - XS1
END DESCRIPTION:
XS GIS Cut Line= 4
      2989086.89      13915418.8      2988299.94     13913648.36
      2986148.77     13913043.34      2985613.06     13913075.34
#Sta/Elev= 30
  2452.8   159.3  2492.8  157.76  2852.8  156.49  3222.8  156.42  3272.8  157.41
  4112.8  155.85  4162.8  156.16  4312.8  155.44  4630.3  155.69  4640.3  156.07
  4730.3  155.15  4780.3  156.26  4940.3  155.89  4960.3  157.11    4984  156.32
 4994.32   155.5 4998.61  152.92 5002.45  153.06 5008.04  156.32  5150.3  155.63
  5250.3  156.17  5810.3  156.07  6270.3  155.61  6280.3  155.97  6490.3  155.35
  6600.3  156.26  6864.9  156.58  7024.9  158.53  7124.9  159.08  7161.6  160.09
#Mann= 5 ,-1 , 0
  2452.8     .99       0  4112.8     .06       0  4960.3     .07       0
 5008.04     .06       0  5810.3     .99       0
#XS Ineff= 2 , 0
       0 4896.75  155.65    5103       0  155.56
Permanent Ineff=
       F       F
Bank Sta=4984,5008.04
Exp/Cntr=0.3,0.1

Type RM Length L Ch R = 1 ,2379    ,0,0,0
BEGIN DESCRIPTION:
Cross Section K155-00-00-X01
END DESCRIPTION:
XS GIS Cut Line= 4
      2988883.24     13912903.41      2988876.12     13912843.78
      2986415.19     13911920.17 2985648.790251613912211.7767183
#Sta/Elev= 30
  4021.4   155.6  4061.4   155.1  4131.4   155.6  4141.4   154.9  4161.4   154.8
  4301.4   154.7  4331.4   155.2  4401.4   154.5  4411.4     155  4681.4   154.4
  4901.4     155  4922.5  154.32  4936.4  155.07    4956  154.83  4975.7  155.89
  4987.4   154.5    4993     153  4995.2  151.59  4997.7  151.02  5004.9  151.74
  5012.7  154.28  5024.7  155.59  5058.7  154.26  5066.3  153.07  5078.3  154.36
  5471.4   153.1    6000  154.41  6131.4   154.8    7510   155.4    7530     156
#Mann= 5 ,-1 , 0
  4021.4     .99       0  4331.4     .06       0  4975.7     .07       0
  5024.7     .06       0    6000     .99       0
Bank Sta=4975.7,5024.7
Exp/Cntr=0.3,0.1

Chan Stop Cuts=-1
Use User Specified Reach Order=0